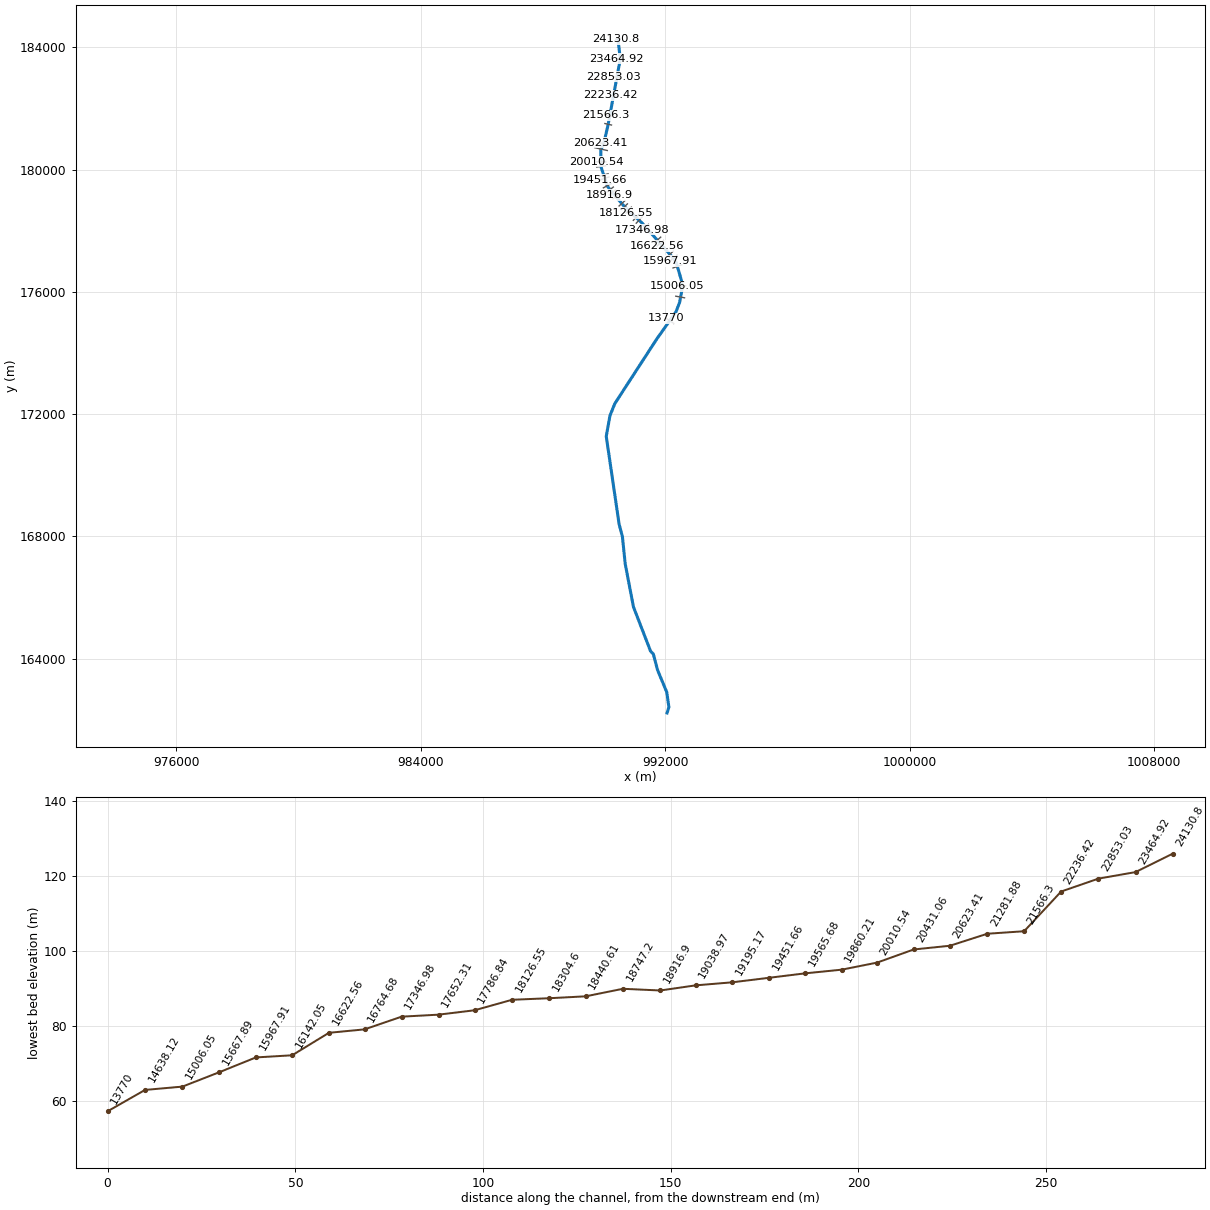
--- Var.prj (project) ---

Proj Title=Var
Current Plan=p02
Default Exp/Contr=0.3,0.1
SI Units
Geom File=g01
Geom File=g02
Flow File=f02
Plan File=p02
Y Axis Title=Elevation
X Axis Title(PF)=Main Channel Distance
X Axis Title(XS)=Station
BEGIN DESCRIPTION:
END DESCRIPTION:
DSS File=dss
DSS Export Rating Curves= 0
DSS Export Rating Curve Sorted= 0
DSS Export Volume Flow Curves= 0
DXF OffsetX= 0
DXF OffsetY= 0
DXF ScaleX= 1
DXF ScaleY= 10

--- Var.p02 (plan) ---

Plan Title=Var_Plan_steady
Program Version=5.01
Short Identifier=steady
Geom File=g01
Flow File=f02
Mixed Flow
K Sum by GR= 0
Std Step Tol= 0.003
Critical Tol= 0.003
Num of Std Step Trials= 20
Max Error Tol= 0.1
Flow Tol Ratio= 0.001
Split Flow NTrial= 30
Split Flow Tol= 0.006
Split Flow Ratio= 0.02
Log Output Level= 0
Friction Slope Method= 1
Unsteady Friction Slope Method= 2
Unsteady Bridges Friction Slope Method= 1
Parabolic Critical Depth
Global Vel Dist= 0 , 0 , 0
Global Log Level= 0
CheckData=True
Encroach Param=-1 ,0,0, 0
BEGIN DESCRIPTION:
This model uses a steady 300 m³/s US BC and a Rating curve for the DS BC to create steady flow conditions in the river.
END DESCRIPTION:
Computation Interval=1MIN
Output Interval=1HOUR
Instantaneous Interval=1HOUR
Mapping Interval=1HOUR
Run HTab= 0
Run UNet= 0
Run Sediment= 0
Run PostProcess= 0
Run WQNet= 0
Run RASMapper= 0
UNET Theta= 1
UNET Theta Warmup= 1
UNET ZTol= 0.006
UNET ZSATol= 0.006
UNET MxIter= 20
UNET Max Iter WO Improvement= 0
UNET MaxInSteps= 0
UNET DtIC= 0
UNET DtMin= 0
UNET MaxCRTS= 20
UNET WFStab= 2
UNET SFStab= 1
UNET WFX= 1
UNET SFX= 1
UNET DSS MLevel= 4
UNET Pardiso=0
UNET DZMax Abort= 30
UNET Use Existing IB Tables=-1
UNET Froude Reduction=False
UNET Froude Limit= 0.8
UNET Froude Power= 4
UNET Time Slicing=0,0, 5
UNET Junction Losses=0
UNET D1 Cores= 0
UNET D2 Coriolis=0
UNET D2 Cores= 0
UNET D2 Theta= 1
UNET D2 Theta Warmup= 1
UNET D2 Z Tol= 0.003
UNET D2 Volume Tol= 0.003
UNET D2 Max Iterations= 20
UNET D2 Equation= 0
UNET D2 RampUpFraction=0.1
UNET D2 TimeSlices= 1
UNET D2 BCVolumeCheck=0
UNET D1D2 MaxIter= 0
UNET D1D2 ZTol=0.003
UNET D1D2 QTol=0.1
UNET D1D2 MinQTol=0.03
DSS File=dss
Write IC File= 0
Write IC File at Fixed DateTime=0
Write IC File at Sim End=0
Echo Input=False
Echo Parameters=False
Echo Output=False
Write Detailed= 0
HDF Write Warmup=0
HDF Write Time Slices=0
HDF Flush=0
HDF Face Node Velocities=0
HDF Compression= 1
HDF Chunk Size= 1
HDF Spatial Parts= 1
HDF Use Max Rows=0
HDF Fixed Rows= 1
Calibration Method= 0
Calibration Iterations= 20
Calibration Max Change=0.05
Calibration Tolerance=0.2
Calibration Maximum=1.5
Calibration Minimum=0.5
Calibration Optimization Method= 1
WQ AD Non Conservative
WQ ULTIMATE=-1
WQ Max Comp Step=1HOUR
WQ Output Interval=15MIN
WQ Output Selected Increments= 0
WQ Output face flow=0
WQ Output face velocity=0
WQ Output face area=0
WQ Output face dispersion=0
WQ Output cell volume=0
WQ Output cell surface area=0
WQ Output cell continuity=0
WQ Output cumulative cell continuity=0
WQ Output face conc=0
WQ Output face dconc_dx=0
WQ Output face courant=0
WQ Output face peclet=0
WQ Output face adv mass=0
WQ Output face disp mass=0
WQ Output cell mass=0
WQ Output cell source sink temp=0
WQ Output nsm pathways=0
WQ Output nsm derived pathways=0
WQ Output MaxMinRange=-1
WQ Daily Max Min Mean=-1
WQ Daily Range=0
WQ Daily Time=0
WQ Create Restart=0
WQ Fixed Restart=0
WQ System Summary=0
WQ Write To DSS=0
WQ Use Fixed Temperature=0
Sorting and Armoring Iterations= 10
XS Update Threshold= 0.02
Bed Roughness Predictor= 0
Hydraulics Update Threshold= 0.02
Energy Slope Method= 1
Volume Change Method= 1
Sediment Retention Method= 0
XS Weighting Method= 0
Number of US Weighted Cross Sections= 1
Number of DS Weighted Cross Sections= 1
Upstream XS Weight=0
Main XS Weight=1
Downstream XS Weight=0
Number of DS XS's Weighted with US Boundary= 1
Upstream Boundary Weight= 1
Weight of XSs Associated with US Boundary= 0
Number of US XS's Weighted with DS Boundary= 1
Downstream Boundary Weight= 0.5
Weight of XSs Associated with DS Boundary= 0.5
Percentile Method= 0
Sediment Output Level= 4
Mass or Volume Output= 0
Output Increment Type= 1
Profile and TS Output Increment= 1
XS Output Flag= 0
XS Output Increment= 10
Write Gradation File= 0
Read Gradation Hotstart= 0
Write HDF5 File= 1
Write DSS Sediment File= 0
SV Curve= 0
Specific Gage Flag= 0

--- Var.p01 (plan) ---

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Plan Title=Var_Plan
Program Version=5.04
Short Identifier=1
Geom File=g01
Flow File=f01
Subcritical Flow
steady flow upstream 300, downstream normal depth
Computation Time Step Use Courant=        0
Computation Time Step Use Time Series=    0
Computation Time Step Count To Double=0
Computation Time Step Max Doubling=0
Computation Time Step Max Halving=0
Computation Time Step Residence Courant=0
UNET 1D Methodology=Finite Difference
Write Binary Output= 1

--- Var.f02 (steady flow) ---

Flow Title=Var_steady
Program Version=5.01
Number of Profiles= 1
Profile Names=PF 1
River Rch & RM=Var,Reach 1         ,24130.8
     300
Boundary for River Rch & Prof#=Var,Reach 1         , 1
Up Type= 3
Up Slope=0.03
Dn Type= 4
Dn Rating Curve # Pts= 41
       0-2.00985     300-.333146304.9336-.116738305.3609-.115824413.3696.0658368
  516.93.2106168638.3517.3691128     738.4888992854.8859.6214872954.8874.7260336
1062.406.83789521173.441.9390888 1273.441.0290051383.774 1.127151484.2261.209142
1584.2251.2911331685.5881.3740381792.752 1.455421892.752 1.531011992.7521.606296
2099.778 1.684632199.7791.7544292299.7781.8245332399.7781.8946372505.684 1.96596
2605.6852.0314922705.6852.0970242805.6842.1625562910.7312.2290023010.7322.290877
 3110.732.3524463210.7282.414016 3315.072.4777193415.0992.5359363515.0982.594458
3615.0982.6526743715.0992.7108913818.9262.7697183918.9272.8251913999.7242.869997
4000.0012.870301
DSS Import GetInterval= 0
DSS Import GetPeak= 0
DSS Import FillOption= 0

--- Var.f01 (steady flow) ---

Flow Title=Var_Flow
Program Version=5.01
Number of Profiles= 1
Profile Names=PF 1
River Rch & RM=Var,1               ,24012.50
     300
Boundary for River Rch & Prof#=Var,1               , 1
Up Type= 3
Up Slope=0.001
Dn Type= 3
Dn Slope=0.001
DSS Import GetInterval= 0
DSS Import GetPeak= 0
DSS Import FillOption= 0

--- Var.g01 (geometry) ---

Geom Title=Var_Geometry
Program Version=5.01

River Reach=Var             ,Reach 1
Reach XY= 30
         990450.         184280.         990530.         183620.
         990130.         181460.         989980.         180820.
         989890.         180650.         989900.         180080.
         990110.         179450.         990280.         179230.
         990680.         178770.         991250.         178240.
         992280.         177080.         992360.         176960.
         992530.         176370.         992540.         176020.
         992470.         175650.         992352.         175342.
         991720.         174450.         990350.         172340.
         990190.         171940.         990070.         171270.
         990490.         168400.         990600.         167980.
         990690.         167100.         990960.         165690.
         991520.         164240.         991610.         164150.
         991750.         163620.         992050.         162900.
         992120.         162410.         992060.         162220.

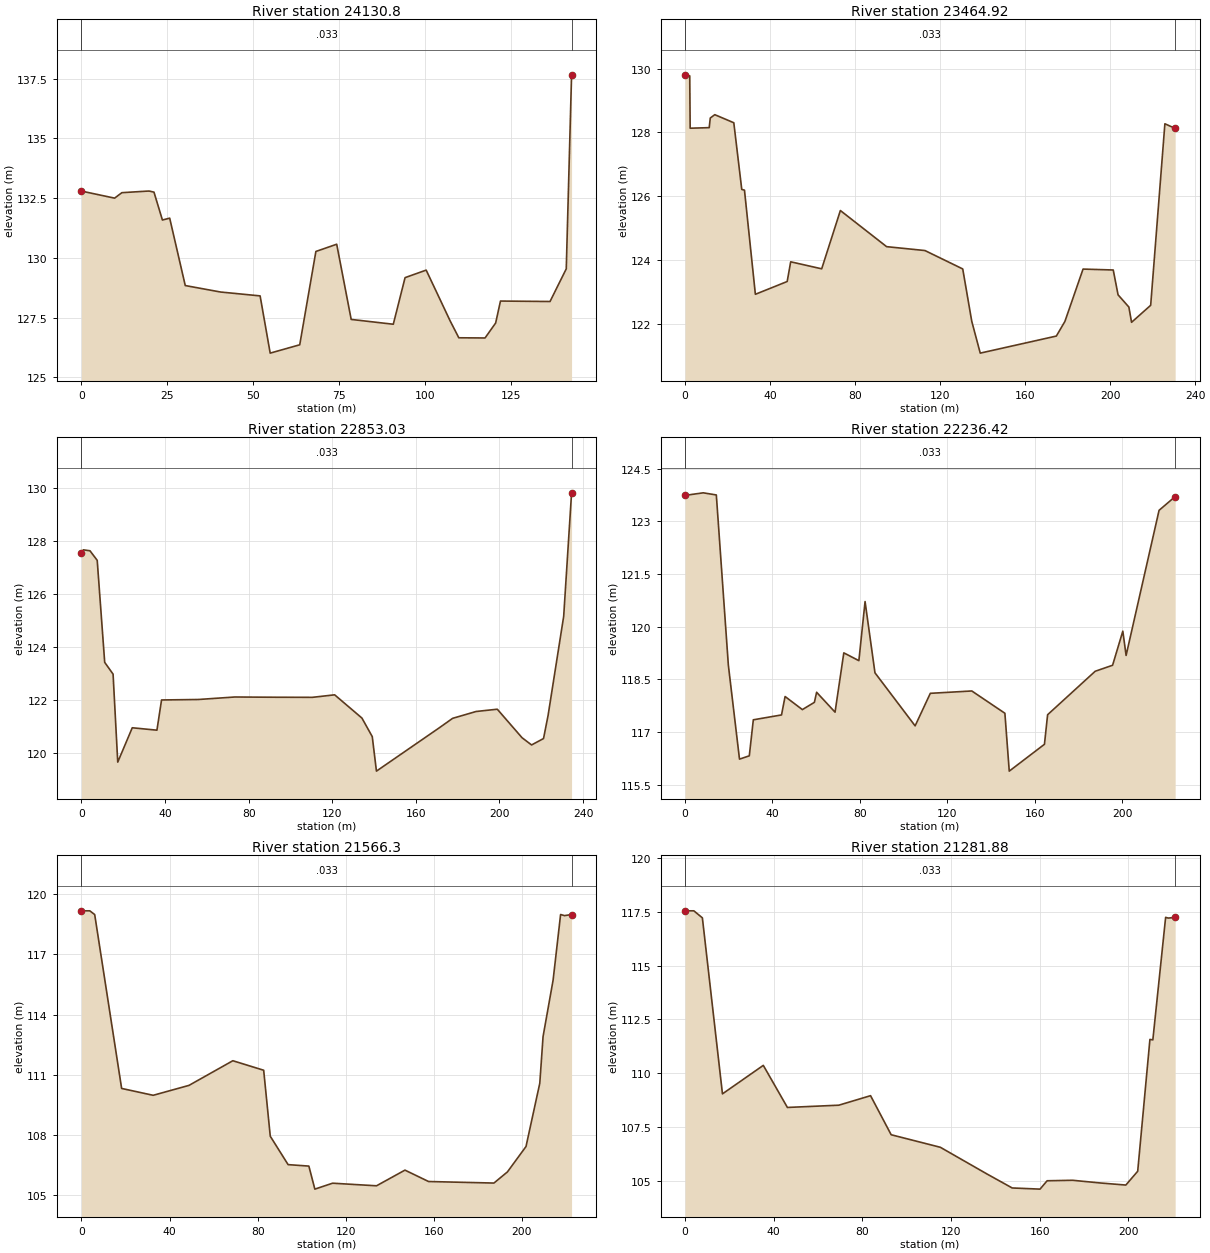
Type RM Length L Ch R = 1 ,24130.8 ,9.939,9.939,9.939
BEGIN DESCRIPTION:
Topo1  0.000
END DESCRIPTION:
XS GIS Cut Line= 3
990520.149784416 184292.37937372         990450.         184280.
990379.850215584 184267.62062628
#Sta/Elev= 28
       0 132.793   9.643 132.498  11.752 132.726   19.33 132.793  19.821 132.791
   21.09 132.748  23.542 131.582  25.656  131.66  30.182  128.84  40.444 128.569
  51.938 128.407  54.867 126.012  63.454 126.361  68.149 130.266  70.887 130.403
  74.199 130.569  78.411 127.422  90.649 127.221  94.071 129.171 100.207 129.486
 107.197 127.354 109.696 126.654 117.319 126.646 120.397 127.272 121.804 128.191
 136.203 128.172 140.924 129.539 142.467 137.658
#Mann= 3 , 0 , 0
       0    .033       0       0    .033       0 142.467    .033       0
Bank Sta=0,142.467
XS Rating Curve= 0 ,0
Exp/Cntr=0.3,0.1

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
Type RM Length L Ch R = 1 ,23464.92,9.869,9.869,9.869
BEGIN DESCRIPTION:
Topo1  665.878
END DESCRIPTION:
XS GIS Cut Line= 3
990645.059757475 183612.57509813990529.998852009183619.994068712
990414.937946543183627.413039293
#Sta/Elev= 29
       0 129.803   2.212 129.771   2.419 128.129  11.381 128.146  11.878 128.448
  14.006 128.553   22.95   128.3  26.691 126.209  27.969 126.186  33.097  122.92
  48.064 123.321  49.713 123.939  64.298 123.719  73.088 125.547  94.846 124.414
 112.882 124.292 130.655 123.715 134.892 122.075 138.892 121.075 174.688  121.61
 178.708 122.067 187.259 123.711 201.464 123.682 203.726 122.904 208.814  122.52
 210.081 122.042 219.074 122.575 225.758 128.268 230.599 128.122
#Mann= 3 , 0 , 0
       0    .033       0       0    .033       0 230.599    .033       0
Bank Sta=0,230.599
XS Rating Curve= 0 ,0
Exp/Cntr=0.3,0.1

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
Type RM Length L Ch R = 1 ,22853.03,9.945,9.945,9.945
BEGIN DESCRIPTION:
Topo1  1277.773
END DESCRIPTION:
XS GIS Cut Line= 3
990525.496182238182999.812708077990409.998596359 183019.99017451
990294.501010479183040.167640943
#Sta/Elev= 29
       0 127.532    .929 127.667   4.105 127.631   7.555 127.271  11.136 123.429
  15.146 122.985  17.378 119.671  24.326 120.965  36.123 120.874  38.334 122.012
  55.919  122.03  73.417 122.124   83.58 122.119  92.913 122.115 110.505 122.111
 121.143 122.206 134.194 121.331 139.141 120.632 141.141 119.332 171.248 120.966
 177.576  121.32 188.814 121.578  198.96 121.664 210.806 120.589 215.359 120.318
 221.074 120.559 223.251 121.427 230.721 125.164 234.493 129.814
#Mann= 3 , 0 , 0
       0    .033       0       0    .033       0 234.493    .033       0
Bank Sta=0,234.493
XS Rating Curve= 0 ,0
Exp/Cntr=0.3,0.1

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
Type RM Length L Ch R = 1 ,22236.42,9.855,9.855,9.855
BEGIN DESCRIPTION:
Topo1  1894.382
END DESCRIPTION:
XS GIS Cut Line= 3
990430.989509829182393.806013829990319.997659474182409.981509841
990209.005809119182426.157005854
#Sta/Elev= 30
       0 123.744    8.35 123.817  14.328 123.756  19.829 118.905  24.931 116.225
  29.415 116.319  31.258 117.346  44.163 117.485  45.793  118.01  53.704 117.637
   59.21 117.844  60.226 118.131  68.665 117.564  72.672 119.255  79.567 119.032
    82.4 120.717  86.932 118.686  105.31 117.173 112.264 118.101 131.252 118.168
 146.392 117.533 148.392 115.883 164.496 116.648 165.944 117.491 187.722  118.73
 195.684 118.901 200.366 119.873  201.87 119.182 216.957 123.318 224.328  123.71
#Mann= 3 , 0 , 0
       0    .033       0       0    .033       0 224.328    .033       0
Bank Sta=0,224.328
XS Rating Curve= 0 ,0
Exp/Cntr=0.3,0.1

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
Type RM Length L Ch R = 1 ,21566.3 ,9.808,9.808,9.808
BEGIN DESCRIPTION:
Topo1  2564.502
END DESCRIPTION:
XS GIS Cut Line= 3
990290.534399541 181747.31263537         990180.181759.975198479
990069.465600459181772.637761587
#Sta/Elev= 25
       0 119.178   3.809 119.178   6.029 118.991  18.256 110.309  32.576 109.967
  48.857 110.463  68.741 111.693  82.739 111.218  85.727 107.924  93.826 106.505
 103.249 106.432  105.97 105.282 114.024 105.578 133.967 105.448 146.871 106.231
 157.593 105.662 187.262 105.585 193.397 106.142 201.831  107.41 208.088 110.571
 209.567 112.898 214.129 115.719 217.531 118.994 219.309 118.938 222.514 118.994
#Mann= 3 , 0 , 0
       0    .033       0       0    .033       0 222.514    .033       0
Bank Sta=0,222.514
XS Rating Curve= 0 ,0
Exp/Cntr=0.3,0.1

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
Type RM Length L Ch R = 1 ,21281.88,9.977,9.977,9.977
BEGIN DESCRIPTION:
Topo1  2848.929
END DESCRIPTION:
XS GIS Cut Line= 3
990241.324150189181455.146472197990133.513283583181479.674388065
990025.702416977181504.202303934
#Sta/Elev= 23
       0  117.54   3.991  117.54   7.831 117.213   16.89 109.037  35.318 110.361
  46.187 108.406   69.38 108.511  83.702 108.953  93.004 107.138 115.183 106.556
 136.372 105.307 147.598 104.666  160.16 104.612 163.359     105 174.855 105.023
 187.427 104.897 198.865 104.801 204.225 105.442 209.738 111.567 211.055 111.544
 216.823 117.236  218.02 117.203 221.131 117.236
#Mann= 3 , 0 , 0
       0    .033       0       0    .033       0 221.131    .033       0
Bank Sta=0,221.131
XS Rating Curve= 0 ,0
Exp/Cntr=0.3,0.1

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
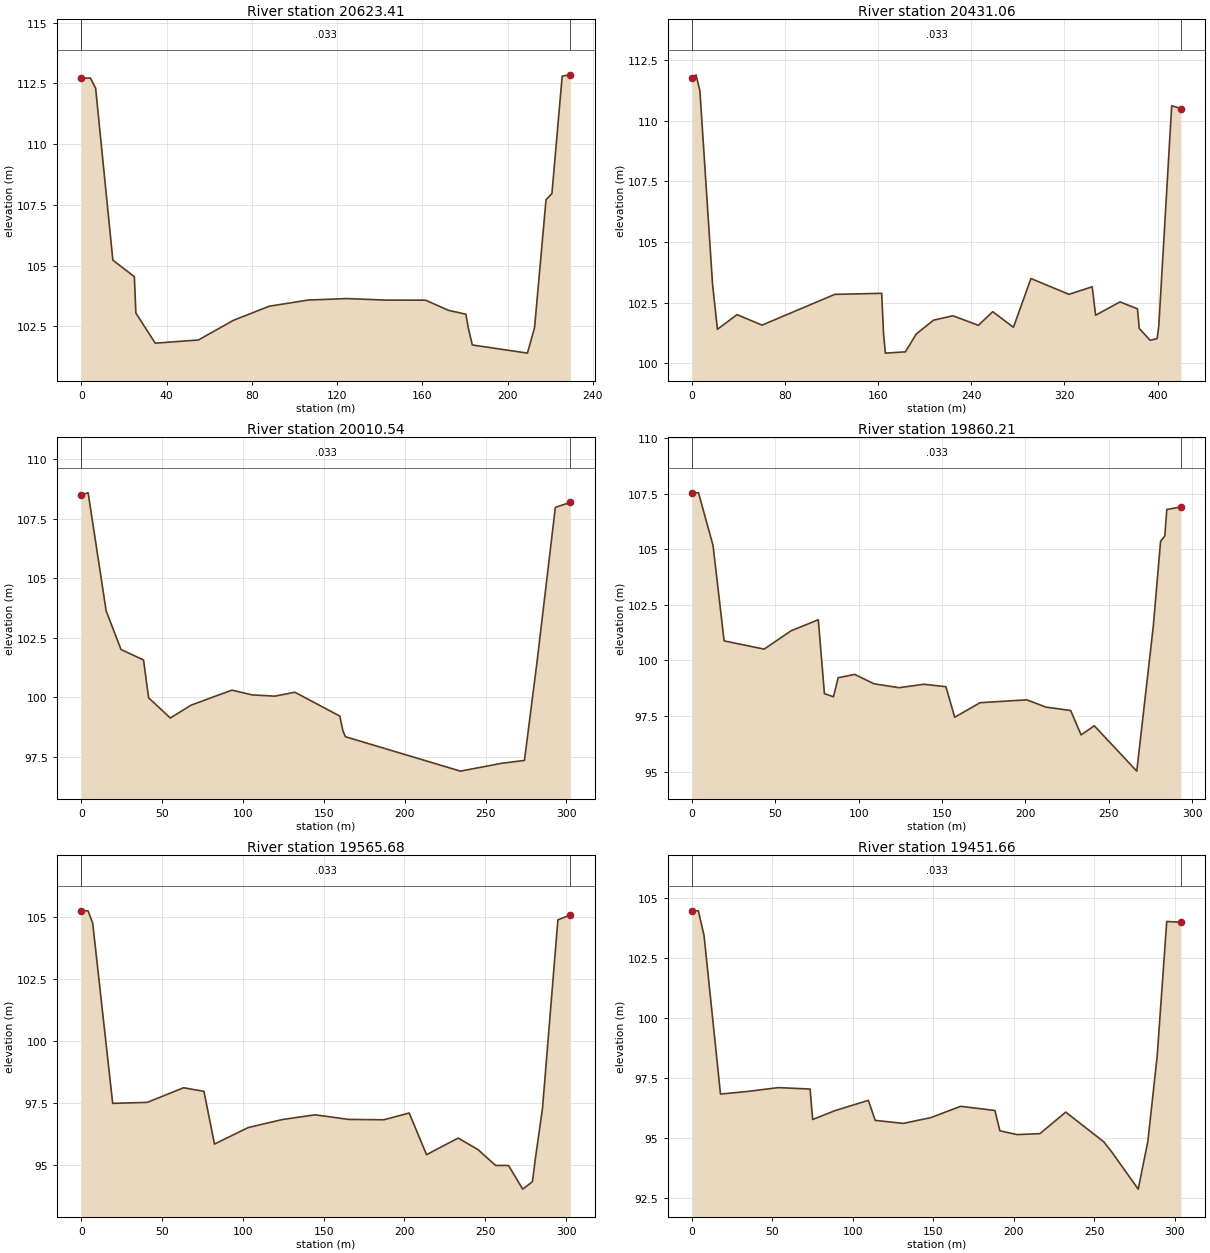
Type RM Length L Ch R = 1 ,20623.41,9.618,9.618,9.618
BEGIN DESCRIPTION:
Topo1  3507.392
END DESCRIPTION:
XS GIS Cut Line= 3
990092.958026981180805.390332246989983.470560554180839.666509806
989873.983094128180873.942687367
#Sta/Elev= 25
       0 112.719    4.24 112.719   6.689 112.306  14.785 105.224  24.869 104.546
  25.577 103.049  34.677 101.809  54.945 101.941  71.274 102.747  88.121 103.329
  106.37 103.584 124.631 103.645 142.987 103.581 161.508  103.58 172.261 103.161
 180.441 103.001 181.608 102.418 183.444 101.736 209.314   101.4 212.653 102.444
 218.034  107.71 220.806 107.966 225.618 112.801 226.065 112.807 229.454 112.852
#Mann= 3 , 0 , 0
       0    .033       0       0    .033       0 229.454    .033       0
Bank Sta=0,229.454
XS Rating Curve= 0 ,0
Exp/Cntr=0.3,0.1

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
Type RM Length L Ch R = 1 ,20431.06,9.78,9.78,9.78
BEGIN DESCRIPTION:
Topo1  3699.746
END DESCRIPTION:
XS GIS Cut Line= 3
990104.236209226180621.457384599989899.344960098180667.651591296
 989694.45371097180713.845797993
#Sta/Elev= 30
       0 111.737   3.486 111.882   6.802 111.228  17.711 103.235  21.874 101.396
  38.706 102.001  60.185 101.569 122.695 102.836 162.975 102.879 164.629 101.175
 166.178 100.415  183.37 100.468  192.68 101.203 207.484 101.773 224.175 101.954
 246.038 101.561 258.355 102.122 276.149  101.48 291.196 103.489 323.837 102.838
 343.832 103.149 346.727 101.976 367.679 102.526 382.713 102.241 384.239 101.431
 393.587 100.944 399.597 101.012 401.036 101.538 412.102 110.607 420.067 110.494
#Mann= 3 , 0 , 0
       0    .033       0       0    .033       0 420.067    .033       0
Bank Sta=0,420.067
XS Rating Curve= 0 ,0
Exp/Cntr=0.3,0.1

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
Type RM Length L Ch R = 1 ,20010.54,9.396,9.396,9.396
BEGIN DESCRIPTION:
Topo1  4120.264
END DESCRIPTION:
XS GIS Cut Line= 3
  990059.8763594180250.952423394989908.671382021180249.929269685
989757.466404642180248.906115976
#Sta/Elev= 23
       0 108.517     4.2 108.594  15.329 103.633  24.524 102.009  38.439  101.57
  41.588  99.981  55.011   99.13  67.841   99.67  80.107  99.978  93.142 100.302
 105.611 100.102 119.576 100.049 132.052 100.214 159.858   99.21 161.779  98.581
 163.306  98.344 234.432  96.898 259.916  97.227 274.025  97.348 281.868 101.522
 293.121 107.981  294.19 108.006 302.416 108.195
#Mann= 3 , 0 , 0
       0    .033       0       0    .033       0 302.416    .033       0
Bank Sta=0,302.416
XS Rating Curve= 0 ,0
Exp/Cntr=0.3,0.1

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
Type RM Length L Ch R = 1 ,19860.21,9.818,9.818,9.818
BEGIN DESCRIPTION:
Topo1  4270.597
END DESCRIPTION:
XS GIS Cut Line= 3
990046.819309857180118.629269499989901.328652514180099.929787717
989755.837995172180081.230305935
#Sta/Elev= 28
       0 107.536    3.93 107.536  12.641 105.166  19.287 100.877  43.305 100.506
  59.522 101.333  75.793 101.827   79.47  98.504  84.902  98.363  87.687  99.218
  97.684  99.369 109.202  98.947 124.336  98.772 139.156  98.927 152.364  98.815
 157.612  97.443 172.862  98.097  200.87  98.225 212.373  97.899   227.2  97.745
 233.463  96.648 241.375  97.059 266.864  95.019 276.728 101.503 281.153 105.357
 283.672 105.596 284.883 106.787 293.374   106.9
#Mann= 3 , 0 , 0
       0    .033       0       0    .033       0 293.374    .033       0
Bank Sta=0,293.374
XS Rating Curve= 0 ,0
Exp/Cntr=0.3,0.1

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
Type RM Length L Ch R = 1 ,19565.68,9.502,9.502,9.502
BEGIN DESCRIPTION:
Topo1  4565.122
END DESCRIPTION:
XS GIS Cut Line= 3
 990130.47200864179860.549713244989984.854275984179819.296465059
989839.236543328179778.043216874
#Sta/Elev= 26
       0  105.25    4.15  105.25   7.031 104.746  19.392  97.486  40.843  97.526
   63.28  98.115  75.881   97.97  82.402  95.844 103.182  96.508 124.379  96.833
 144.667  97.024 165.494  96.838 187.239  96.824 202.919  97.096 213.679  95.416
  233.25  96.087  245.52  95.621 256.414  94.982 264.412   94.98 273.218  94.027
 279.216  94.327 280.918  95.197 285.459  97.291 294.972 104.885  295.66 104.903
 302.696 105.085
#Mann= 3 , 0 , 0
       0    .033       0       0    .033       0 302.696    .033       0
Bank Sta=0,302.696
XS Rating Curve= 0 ,0
Exp/Cntr=0.3,0.1

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
Type RM Length L Ch R = 1 ,19451.66,9.865,9.865,9.865
BEGIN DESCRIPTION:
Topo1  4679.140
END DESCRIPTION:
XS GIS Cut Line= 3
990159.010883454179757.151272979990014.746338552 179709.26342531
 989870.48179365179661.375577641
#Sta/Elev= 27
       0 104.466   3.971 104.466   7.501  103.44  17.735   96.82  34.671   96.93
   53.71   97.09  73.441   97.03  75.026  95.759  88.752  96.125 109.651  96.558
 113.931  95.722 131.387  95.597 148.418  95.836 167.022  96.309  188.33  96.135
 191.437  95.287 202.122   95.13 216.322  95.169 232.358  96.068 256.089  94.824
 260.787  94.421 277.442  92.854 283.441  94.854 289.231  98.412 295.161  104.02
  296.14 104.017 304.009 103.992
#Mann= 3 , 0 , 0
       0    .033       0       0    .033       0 304.009    .033       0
Bank Sta=0,304.009
XS Rating Curve= 0 ,0
Exp/Cntr=0.3,0.1

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
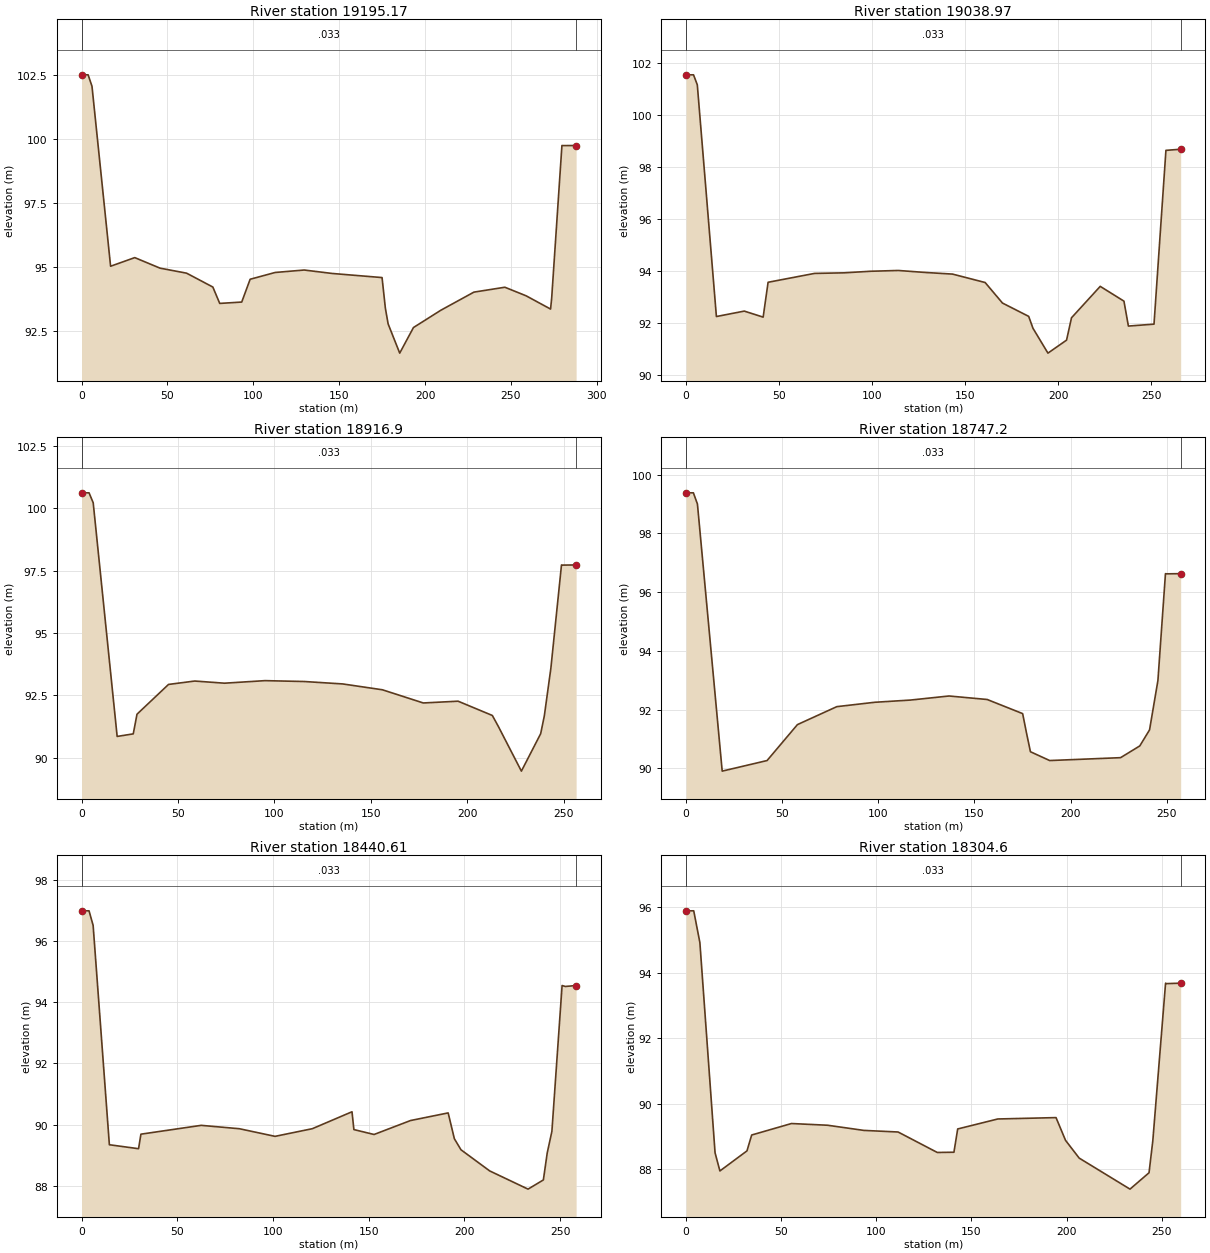
Type RM Length L Ch R = 1 ,19195.17,9.762,9.762,9.762
BEGIN DESCRIPTION:
Topo1  4935.631
END DESCRIPTION:
XS GIS Cut Line= 3
990230.612115753 179536.91658747990103.685143988179468.944568036
989976.758172223179400.972548602
#Sta/Elev= 28
       0 102.517   3.834 102.517    6.09 102.071  16.926  95.036  30.992  95.373
  45.713  94.961  61.162  94.765  76.451  94.223   80.46  93.583  93.266  93.636
  98.172  94.527 112.722  94.792 129.627  94.888  145.97  94.753 174.964  94.593
 176.896  93.395 178.499  92.783 185.248   91.64 193.248   92.64 209.213  93.317
 228.441  94.024 246.462  94.215 258.807  93.881 273.078  93.362 273.729  93.799
 279.685  99.754 280.571  99.751 287.962  99.754
#Mann= 3 , 0 , 0
       0    .033       0       0    .033       0 287.962    .033       0
Bank Sta=0,287.962
XS Rating Curve= 0 ,0
Exp/Cntr=0.3,0.1

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
Type RM Length L Ch R = 1 ,19038.97,9.39,9.39,9.39
BEGIN DESCRIPTION:
Topo1  5091.836
END DESCRIPTION:
XS GIS Cut Line= 3
990302.241440382179426.697859952990197.213044206179345.344346952
990092.184648031179263.990833953
#Sta/Elev= 27
       0 101.534   4.014 101.534   6.041  101.15  16.303  92.234  31.274  92.443
  41.415  92.211  44.068  93.552  68.997  93.893  84.792  93.915  99.226  93.976
 113.982  94.006 128.192  93.931 143.127  93.867 160.661  93.543 169.965  92.753
 184.057   92.24 186.351  91.783 194.398  90.826 204.399  91.326 207.055  92.186
 222.484  93.395 235.224  92.826 237.614  91.867 251.374  91.941 257.778  98.628
 259.509  98.637 265.701  98.671
#Mann= 3 , 0 , 0
       0    .033       0       0    .033       0 265.701    .033       0
Bank Sta=0,265.701
XS Rating Curve= 0 ,0
Exp/Cntr=0.3,0.1

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
Type RM Length L Ch R = 1 ,18916.9 ,9.982,9.982,9.982
BEGIN DESCRIPTION:
Topo1  5213.902
END DESCRIPTION:
XS GIS Cut Line= 3
990367.219396419179328.298351946990268.548494132179246.359294097
990169.877591845179164.420236248
#Sta/Elev= 24
       0 100.619   3.903 100.619   6.059  100.22  18.481  90.851  26.833  90.954
  28.771  91.742  45.115  92.936  58.716  93.072  74.144  92.986  95.131  93.088
 115.502  93.053 135.452  92.956 156.017  92.722 177.248  92.193 195.284  92.264
 213.049  91.692 216.138  91.256 228.115   89.46 238.115   90.96 240.008  91.672
 243.414  93.591 248.915  97.727 249.397  97.721 256.514  97.727
#Mann= 3 , 0 , 0
       0    .033       0       0    .033       0 256.514    .033       0
Bank Sta=0,256.514
XS Rating Curve= 0 ,0
Exp/Cntr=0.3,0.1

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
Type RM Length L Ch R = 1 ,18747.2 ,9.89,9.89,9.89
BEGIN DESCRIPTION:
Topo1  5383.607
END DESCRIPTION:
XS GIS Cut Line= 3
990482.953604323179208.527222899990385.876112819179124.123887181
990288.798621316179039.720551462
#Sta/Elev= 22
       0  99.381   3.812  99.381   5.919  99.001    18.8   89.91  42.145   90.27
  57.925  91.493  78.414  92.104  98.146  92.253  116.83  92.329 136.777  92.467
 156.623  92.348 175.076  91.867 177.084  91.207 179.133   90.57 189.131   90.27
 226.011  90.368  236.01  90.768 241.088  91.314 245.434  92.993  249.36   96.63
 250.068  96.624 257.277   96.63
#Mann= 3 , 0 , 0
       0    .033       0       0    .033       0 257.277    .033       0
Bank Sta=0,257.277
XS Rating Curve= 0 ,0
Exp/Cntr=0.3,0.1

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
Type RM Length L Ch R = 1 ,18440.61,9.715,9.715,9.715
BEGIN DESCRIPTION:
Topo1  5690.190
END DESCRIPTION:
XS GIS Cut Line= 3
 990680.79447581178980.196574774990585.161593042178893.354566262
990489.528710274 178806.51255775
#Sta/Elev= 25
       0   96.98   3.924   96.98    6.06  96.506  14.549  89.347  29.795  89.218
  31.025  89.692  62.517   89.98  82.437   89.87 101.082  89.621 120.565  89.871
 141.279  90.423 142.273  89.842 152.801  89.682 171.843  90.137 191.504  90.386
 194.758  89.542 198.204  89.183 213.204  88.493 233.232  87.899 241.232  88.199
 243.234  89.074 245.694  89.787 251.012  94.542 252.712  94.512 258.357  94.542
#Mann= 3 , 0 , 0
       0    .033       0       0    .033       0 258.357    .033       0
Bank Sta=0,258.357
XS Rating Curve= 0 ,0
Exp/Cntr=0.3,0.1

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
Type RM Length L Ch R = 1 ,18304.6 ,9.892,9.892,9.892
BEGIN DESCRIPTION:
Topo1  5826.205
END DESCRIPTION:
XS GIS Cut Line= 3
990762.761749328178875.391789655990668.256368042178786.147493942
990573.750986756178696.903198229
#Sta/Elev= 24
       0  95.892   4.034  95.892   7.267  94.921  15.244    88.5  17.795  87.945
  32.025  88.559  34.486  89.043  55.382  89.394  74.308  89.342  93.469  89.184
 111.448  89.135 132.046   88.51 140.794  88.517 142.765  89.228  163.85  89.533
 194.449  89.575  199.45   88.88 206.622  88.338 233.329   87.39 243.329   87.89
 245.321  88.868 252.024  93.682 252.524  93.668 259.967  93.682
#Mann= 3 , 0 , 0
       0    .033       0       0    .033       0 259.967    .033       0
Bank Sta=0,259.967
XS Rating Curve= 0 ,0
Exp/Cntr=0.3,0.1

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
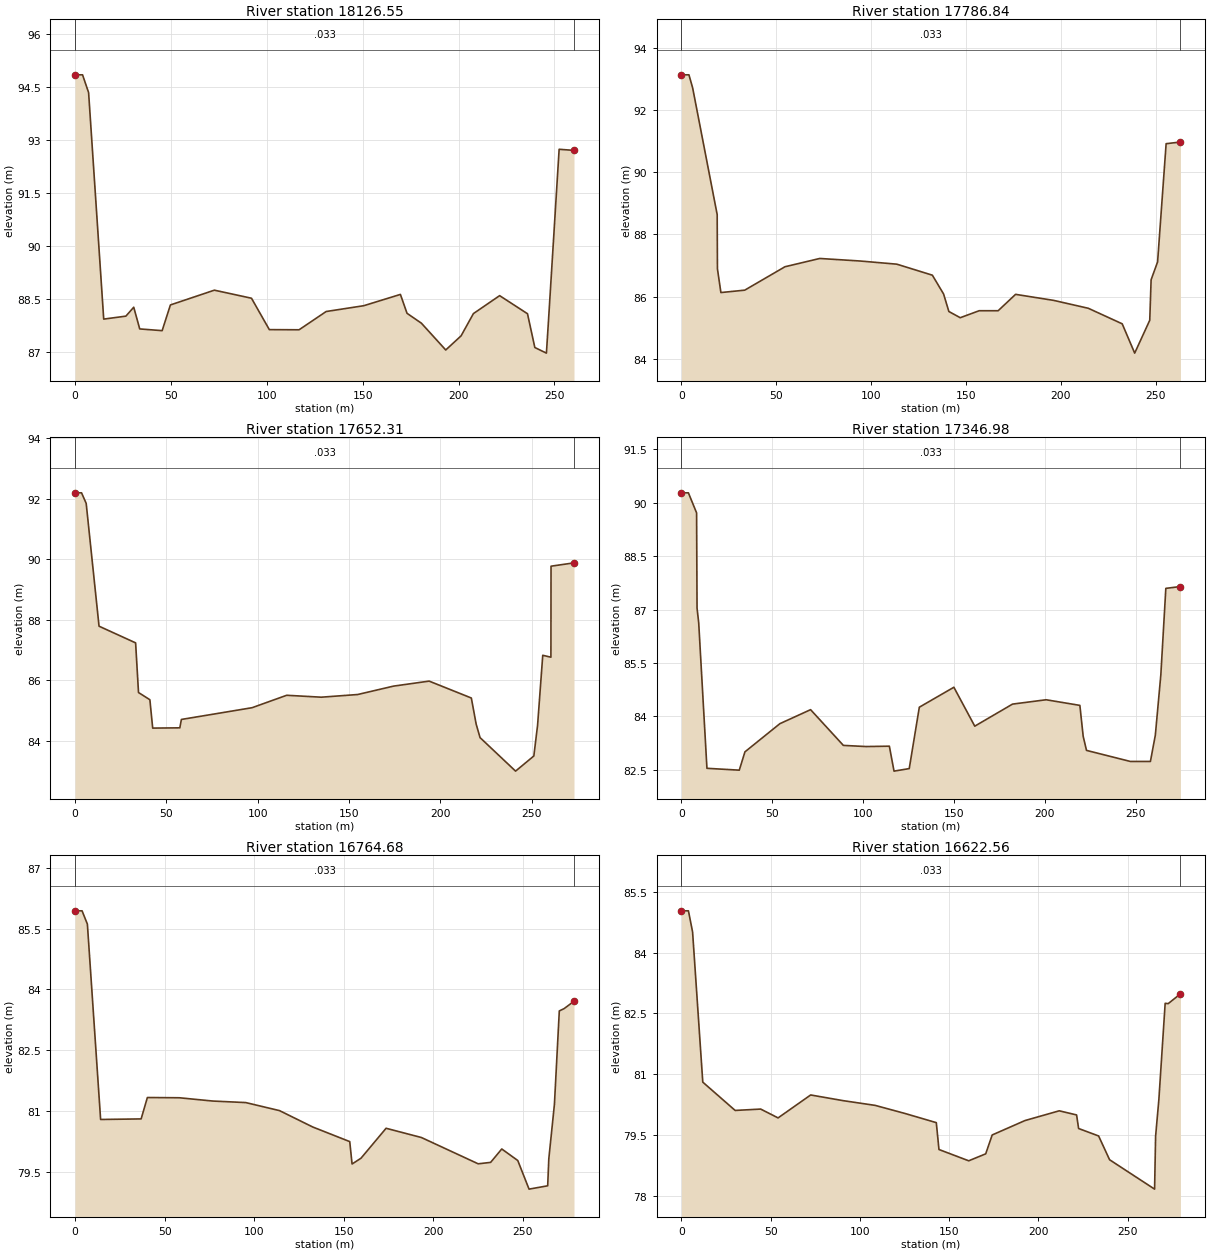
Type RM Length L Ch R = 1 ,18126.55,9.991,9.991,9.991
BEGIN DESCRIPTION:
Topo1  6004.250
END DESCRIPTION:
XS GIS Cut Line= 3
990891.697397259178768.691391282990804.305288119178672.331559335
990716.913178979178575.971727388
#Sta/Elev= 30
       0  94.857   3.942  94.857   7.099  94.355  14.974  87.942  26.535  88.026
   30.63  88.278  33.754  87.664  45.439  87.615  49.754  88.343   72.67  88.761
  92.021  88.533 101.332  87.644 116.842   87.64 130.963  88.157 150.552  88.321
 169.666  88.641  173.12  88.106 180.612  87.826 193.304  87.068 201.303  87.468
 207.721  88.097 207.731  88.098 221.403  88.606 235.928  88.094 239.754  87.138
 245.795  86.979 247.039   88.04 252.427  92.749 253.174  92.746 260.173  92.718
#Mann= 3 , 0 , 0
       0    .033       0       0    .033       0 260.173    .033       0
Bank Sta=0,260.173
XS Rating Curve= 0 ,0
Exp/Cntr=0.3,0.1

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
Type RM Length L Ch R = 1 ,17786.84,9.609,9.609,9.609
BEGIN DESCRIPTION:
Topo1  6343.960
END DESCRIPTION:
XS GIS Cut Line= 3
 991134.21701036178530.533837097991045.374051856178433.581237562
990956.531093352178336.628638027
#Sta/Elev= 28
       0  93.148   3.943  93.148    5.89   92.73  18.828  88.642  18.962  86.894
  20.787  86.128  33.348  86.205  54.567   86.96  72.895  87.227  94.223  87.145
 113.521  87.043 132.241  86.688 138.157  86.082 140.936  85.517 146.935  85.317
 156.912  85.542 166.912  85.542   176.1   86.07 196.144  85.876 214.428  85.621
   232.3   85.12 238.877  84.175 246.818  85.235 247.536  86.541 250.952  87.117
 255.449  90.928 256.354  90.934 263.004  90.981
#Mann= 3 , 0 , 0
       0    .033       0       0    .033       0 263.004    .033       0
Bank Sta=0,263.004
XS Rating Curve= 0 ,0
Exp/Cntr=0.3,0.1

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
Type RM Length L Ch R = 1 ,17652.31,9.849,9.849,9.849
BEGIN DESCRIPTION:
Topo1  6478.496
END DESCRIPTION:
XS GIS Cut Line= 3
991238.941474906178442.717765358 991145.15937764178343.356560124
991051.377280373178243.995354891
#Sta/Elev= 29
       0  92.194   3.583  92.194   6.129  91.846  13.172  87.789  33.199  87.238
  34.784  85.598  41.011   85.36  42.552  84.423  57.307  84.432  57.398  84.429
   58.27  84.709  77.492  84.901  96.984  85.097 115.929  85.507 134.892  85.444
 154.773  85.532  174.46   85.81 193.937  85.975 217.037  85.417 219.692  84.553
  221.82  84.109 241.267  83.002 251.268  83.502 253.316  84.515  256.15  86.828
 260.621  86.765 260.681  89.771 262.323  89.785 273.259  89.881
#Mann= 3 , 0 , 0
       0    .033       0       0    .033       0 273.259    .033       0
Bank Sta=0,273.259
XS Rating Curve= 0 ,0
Exp/Cntr=0.3,0.1

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
Type RM Length L Ch R = 1 ,17346.98,9.869,9.869,9.869
BEGIN DESCRIPTION:
Topo1  6783.821
END DESCRIPTION:
XS GIS Cut Line= 3
991451.212969188178205.957235633991347.670582433178115.691985994
991244.128195679178025.426736355
#Sta/Elev= 30
       0  90.277   3.824  90.277   8.331  89.715   8.582  87.039   9.492  86.633
  14.031  82.545  31.834  82.493  34.955  83.007  54.193  83.798  71.099  84.191
  89.143  83.188 101.597  83.156 114.462  83.166 117.027  82.466 125.407  82.537
 130.959   84.26 149.981   84.82 161.478  83.728 182.269  84.347  200.75  84.469
 219.347  84.311  221.17  83.444 222.995  83.048 247.183  82.737 258.183  82.737
 260.893  83.476 263.916  85.165 266.673  87.595  267.71  87.602 274.727  87.647
#Mann= 3 , 0 , 0
       0    .033       0       0    .033       0 274.727    .033       0
Bank Sta=0,274.727
XS Rating Curve= 0 ,0
Exp/Cntr=0.3,0.1

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
Type RM Length L Ch R = 1 ,16764.68,9.475,9.475,9.475
BEGIN DESCRIPTION:
Topo1  7366.122
END DESCRIPTION:
XS GIS Cut Line= 3
991851.213460953177786.675322629991746.575952725177694.766452002
991641.938444497177602.857581376
#Sta/Elev= 27
       0  85.941   3.952  85.941   6.918  85.613  14.304  80.791  36.915  80.805
   40.41  81.333  58.216  81.327   76.91  81.246  95.331  81.208 114.155   81.01
 132.685  80.606 153.359  80.245 154.666  79.692 159.653  79.835 173.648  80.574
 193.366  80.346 225.046  79.697 231.999  79.732 238.223  80.063 247.159  79.778
 253.448  79.072 263.855  79.154 264.479  79.819 267.617  81.166  270.34   83.47
  273.01  83.527  278.54  83.709
#Mann= 3 , 0 , 0
       0    .033       0       0    .033       0  278.54    .033       0
Bank Sta=0,278.54
XS Rating Curve= 0 ,0
Exp/Cntr=0.3,0.1

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
Type RM Length L Ch R = 1 ,16622.56,9.806,9.806,9.806
BEGIN DESCRIPTION:
Topo1  7508.249
END DESCRIPTION:
XS GIS Cut Line= 3
991945.293046077 177674.35560735991837.358318059177585.450944594
991729.423590042177496.546281839
#Sta/Elev= 28
       0   85.03   3.912   85.03   6.239  84.508  11.951  80.802  30.098  80.103
  44.399  80.137  54.152  79.919  72.417  80.485   90.73  80.344 108.563  80.228
 125.229  80.029 142.828  79.802 144.325  79.139 160.993   78.86 170.512  79.032
 174.159  79.498 192.557  79.854 211.724  80.094 221.451  79.992 222.592  79.657
 233.795  79.473  239.95  78.886 265.172  78.161 265.738  79.465 267.581  80.379
 271.095  82.747 272.783  82.739  279.67  82.981
#Mann= 3 , 0 , 0
       0    .033       0       0    .033       0  279.67    .033       0
Bank Sta=0,279.67
XS Rating Curve= 0 ,0
Exp/Cntr=0.3,0.1

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
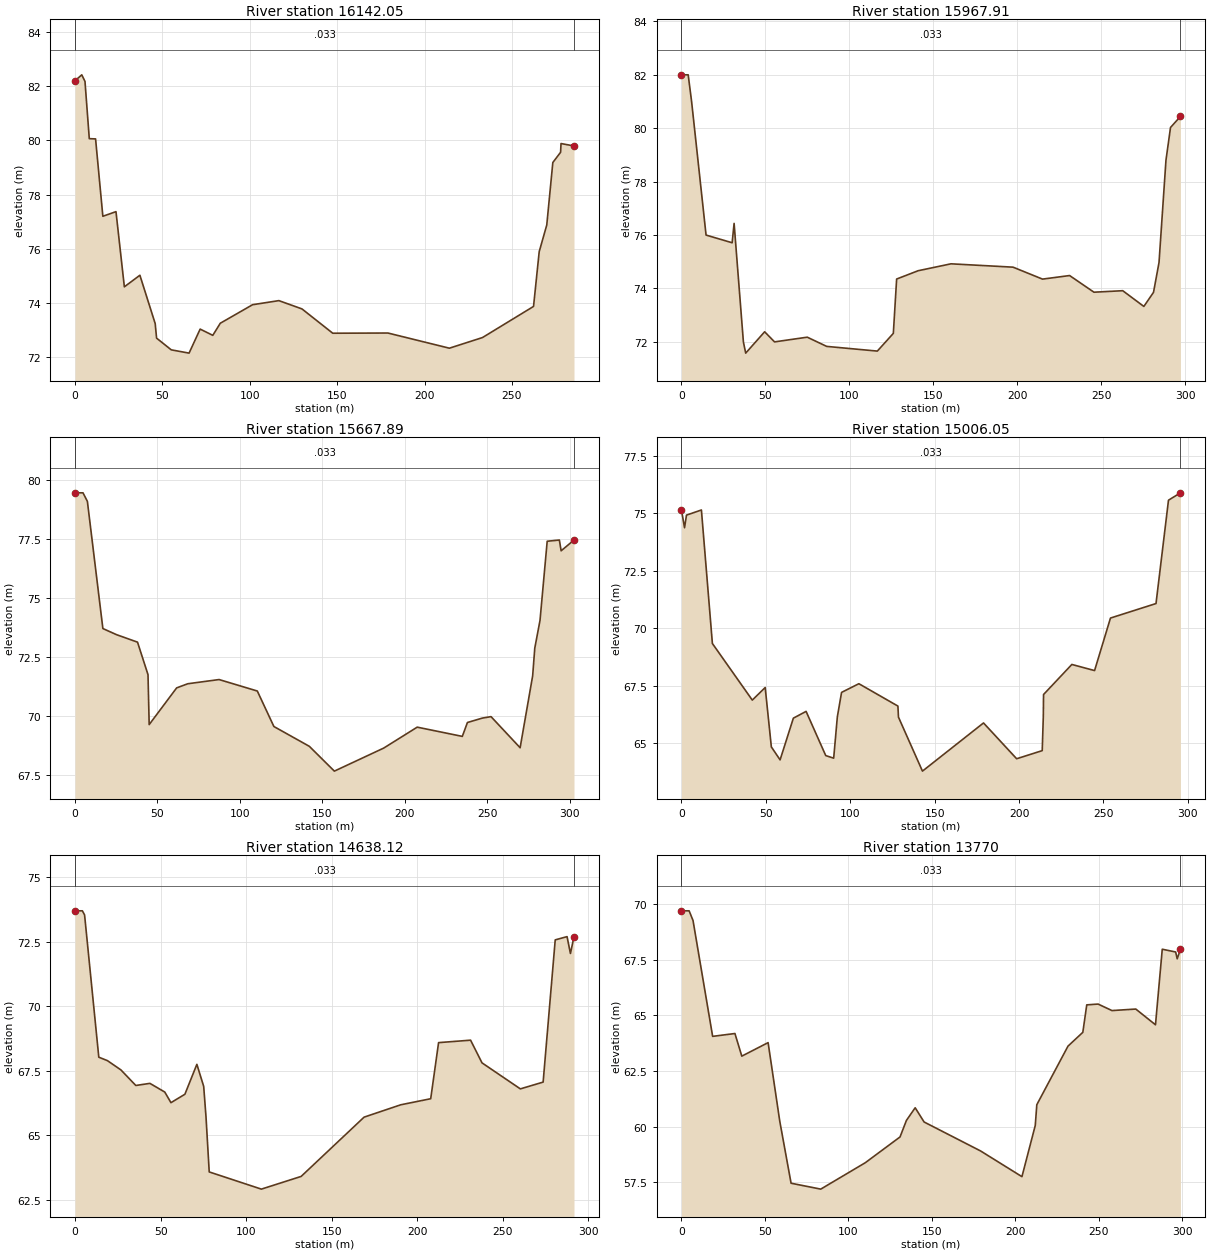
Type RM Length L Ch R = 1 ,16142.05,9.674,9.674,9.674
BEGIN DESCRIPTION:
Topo1  7988.752
END DESCRIPTION:
XS GIS Cut Line= 3
992262.453052582177329.369139495992158.638119669177231.361880331
992054.823186756177133.354621168
#Sta/Elev= 30
       0  82.196   3.882  82.417    5.72  82.174   8.181  80.063  11.781  80.054
  15.945  77.201  23.454  77.372  28.247    74.6   37.14  75.027  45.902  73.242
  46.687  72.708  55.088  72.276  65.278  72.155  71.621  73.041   78.86  72.811
  83.147  73.257 101.614   73.94 116.656  74.091 129.889  73.785 147.491  72.889
 179.077  72.896 214.228  72.337 233.201   72.73 262.387  73.877  265.63  75.897
 269.956  76.879 273.425  79.184 277.873  79.561 278.111  79.883 285.537  79.794
#Mann= 3 , 0 , 0
       0    .033       0       0    .033       0 285.537    .033       0
Bank Sta=0,285.537
XS Rating Curve= 0 ,0
Exp/Cntr=0.3,0.1

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
Type RM Length L Ch R = 1 ,15967.91,9.678,9.678,9.678
BEGIN DESCRIPTION:
Topo1  8162.893
END DESCRIPTION:
XS GIS Cut Line= 3
992384.519776199177183.384787316992265.661339232177094.338660768
992146.802902264177005.292534221
#Sta/Elev= 28
       0      82   4.004      82    6.01  81.015  14.648  75.998  30.173   75.71
  31.335  76.435  36.867  71.997   38.24  71.576  49.523  72.376  55.406  71.997
   74.89  72.173  86.443  71.828 116.602  71.652 126.118  72.316 128.087  74.351
 140.865  74.662 160.444  74.921 197.374  74.796 214.922  74.348 231.041  74.482
 245.532  73.858 262.673  73.914 275.238  73.325 280.988  73.853 284.265   74.97
 288.399  78.801 291.111  80.028 297.028  80.442
#Mann= 3 , 0 , 0
       0    .033       0       0    .033       0 297.028    .033       0
Bank Sta=0,297.028
XS Rating Curve= 0 ,0
Exp/Cntr=0.3,0.1

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
Type RM Length L Ch R = 1 ,15667.89,9.878,9.878,9.878
BEGIN DESCRIPTION:
Topo1  8462.918
END DESCRIPTION:
XS GIS Cut Line= 3
992540.439483719176881.132349678992397.986150406176830.034623984
992255.532817094176778.936898291
#Sta/Elev= 30
       0  79.436   4.853  79.436   7.519  79.074  16.913  73.689  25.174   73.43
  37.925  73.113  44.289  71.736  45.003  69.622  61.665  71.176  68.414  71.351
    87.4  71.529 110.594  71.043 120.649   69.54 142.133  68.702 157.323  67.651
 187.245  68.626 207.572  69.513 234.933  69.122 238.046   69.71  247.12  69.897
 252.346  69.959 270.002  68.641 277.607  71.686 278.889  72.858 282.069  74.035
 286.421  77.385  287.79  77.395 293.809  77.437 294.876  76.981  302.68  77.437
#Mann= 3 , 0 , 0
       0    .033       0       0    .033       0  302.68    .033       0
Bank Sta=0,302.68
XS Rating Curve= 0 ,0
Exp/Cntr=0.3,0.1

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
Type RM Length L Ch R = 1 ,15006.05,9.944,9.944,9.944
BEGIN DESCRIPTION:
Topo1  9124.758
END DESCRIPTION:
XS GIS Cut Line= 3
992669.039850684176192.383600121992521.270155671 176188.56859896
992373.500460658176184.753597799
#Sta/Elev= 30
       0  75.1381.830994  74.366 2.97998  74.91511.82199  75.138  18.328  69.334
41.96599  66.87449.61099   67.42  53.258  64.83958.43799  64.275  66.297  66.088
  73.842  66.38385.47899  64.462  90.187  64.349  92.355  66.14694.85599  67.208
 105.105  67.586 128.237  66.614 128.567  66.134  142.78  63.786 178.956   65.88
 198.587  64.324 213.736  64.677 214.386  66.162 214.518  67.116 231.291  68.423
 244.751  68.157 254.175   70.44 281.152  71.071 288.546  75.564 295.637  75.884
#Mann= 3 , 0 , 0
       0    .033       0       0    .033       0 295.637    .033       0
Bank Sta=0,295.637
XS Rating Curve= 0 ,0
Exp/Cntr=0.3,0.1

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
Type RM Length L Ch R = 1 ,14638.12,9.978,9.978,9.978
BEGIN DESCRIPTION:
Topo1  9492.683
END DESCRIPTION:
XS GIS Cut Line= 3
992632.175973572175802.265790316992488.795316343175828.555505257
992345.414659114175854.845220199
#Sta/Elev= 29
       0  73.697   4.314  73.697   5.602  73.538  13.911   68.02  18.935  67.887
  26.812  67.528  35.537  66.923  43.765  67.005  52.459  66.668  56.068  66.256
  64.218  66.583  71.209  67.743  75.194  66.888  76.561  65.689  78.424   63.57
 108.893  62.903 132.134  63.396 168.912  65.695 190.325  66.174 207.825  66.409
 212.424  68.585 231.125   68.68 237.799    67.8 260.199  66.791 273.508  67.054
 280.574   72.57 287.488  72.696 289.458  72.043 291.541  72.696
#Mann= 3 , 0 , 0
       0    .033       0       0    .033       0 291.541    .033       0
Bank Sta=0,291.541
XS Rating Curve= 0 ,0
Exp/Cntr=0.3,0.1

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
Type RM Length L Ch R = 1 ,13770   ,9.854,9.854,9.854
BEGIN DESCRIPTION:
Topo1  10360.880
END DESCRIPTION:
XS GIS Cut Line= 3
992278.001436483174964.151311982992153.951880729175047.439850911
992029.902324974 175130.72838984
#Sta/Elev= 30
       0  69.696   4.585  69.696   6.921  69.265  18.676   64.06  32.026  64.188
  36.137  63.172  51.892  63.779  58.878  60.249  65.648  57.467   83.42  57.202
 110.123  58.389 130.887  59.544 134.734  60.288 139.963  60.854 145.303  60.216
 179.105  58.917 203.902  57.762 211.888  60.063 212.807  60.992 231.491  63.622
 240.364  64.241 242.714  65.474 249.516   65.51 257.806  65.218 272.086  65.286
 283.874   64.58 287.928  67.972 295.952  67.848 296.881  67.542 298.832  67.972
#Mann= 3 , 0 , 0
       0    .033       0       0    .033       0 298.832    .033       0
Bank Sta=0,298.832
XS Rating Curve= 0 ,0
Exp/Cntr=0.3,0.1

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