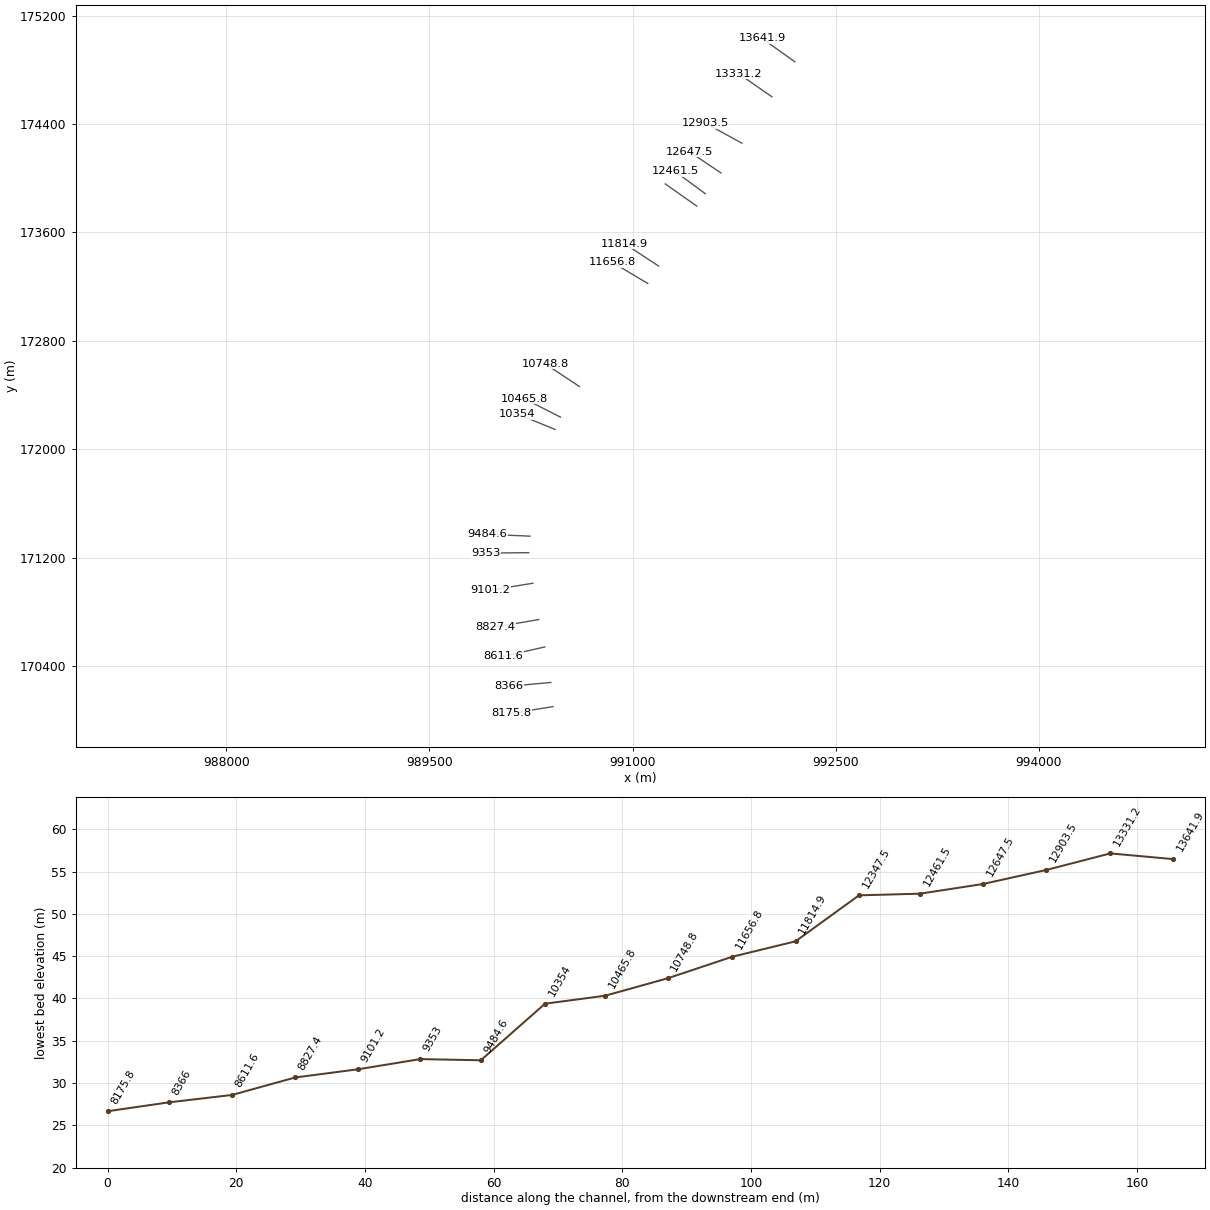
HEC-RAS study Var.prj: Var

--- Var.g01 (geometry) --- (continued)

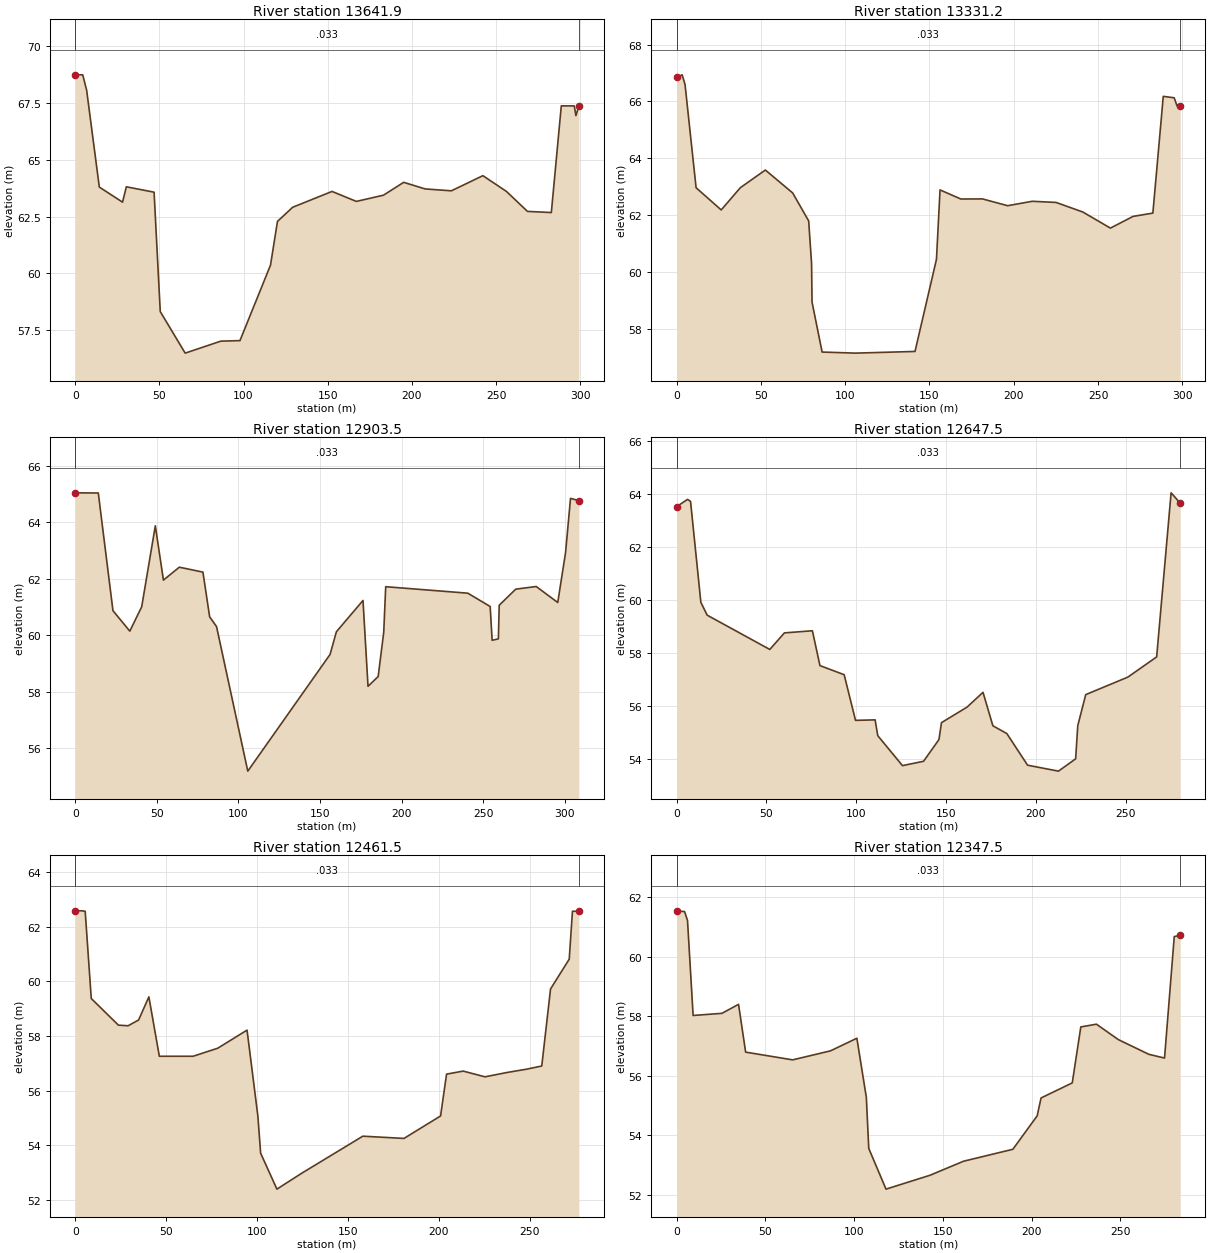
Type RM Length L Ch R = 1 ,13641.9 ,9.709,9.709,9.709
BEGIN DESCRIPTION:
Topo1  10488.943
END DESCRIPTION:
XS GIS Cut Line= 3
992198.729515143174858.542415692992076.849458771174945.274188156
991954.969402398 175032.00596062
#Sta/Elev= 28
       0  68.751   4.454  68.751   6.778  68.077  14.316  63.802  28.104  63.137
  30.364  63.814  46.844  63.577  50.513  58.311  65.317  56.481  86.505  57.009
  97.856  57.033 115.995  60.358 120.137  62.288  129.17  62.912 152.548   63.61
 166.995   63.17 183.098  63.444 195.117  64.011 207.881   63.72 223.445  63.637
 242.153  64.305 256.148   63.61 268.626   62.73 282.812  62.679  288.73  67.383
 296.448   67.38 297.413  66.953 299.179  67.383
#Mann= 3 , 0 , 0
       0    .033       0       0    .033       0 299.179    .033       0
Bank Sta=0,299.179
XS Rating Curve= 0 ,0
Exp/Cntr=0.3,0.1

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
Type RM Length L Ch R = 1 ,13331.2 ,9.947,9.947,9.947
BEGIN DESCRIPTION:
Topo1  10799.605
END DESCRIPTION:
XS GIS Cut Line= 3
992028.478447718174600.895614331991905.717874505174686.005024307
991782.957301292174771.114434284
#Sta/Elev= 29
       0  66.843   3.311  66.936   5.028  66.595  11.587  62.966  26.484  62.186
  37.817  62.967  52.662  63.589  68.881  62.783  78.359  61.801   80.08  60.303
  80.362  58.946  86.337   57.19 106.107  57.152 141.439  57.211 154.159  60.448
 156.285   62.89 168.637   62.57 181.474  62.573 196.384  62.335 210.963   62.49
 225.072   62.45  240.94  62.114 257.343  61.547 270.788  61.959 282.529  62.075
 288.695  66.179 295.171  66.129 296.833  65.849 298.755   65.83
#Mann= 3 , 0 , 0
       0    .033       0       0    .033       0 298.755    .033       0
Bank Sta=0,298.755
XS Rating Curve= 0 ,0
Exp/Cntr=0.3,0.1

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
Type RM Length L Ch R = 1 ,12903.5 ,9.846,9.846,9.846
BEGIN DESCRIPTION:
Topo1  11227.385
END DESCRIPTION:
XS GIS Cut Line= 3
991806.548373794174258.345751511991671.353250727174332.706501454
 991536.15812766174407.067251398
#Sta/Elev= 30
       0  65.036  14.141   65.03   23.12   60.87  33.444  60.146  40.729  61.007
  49.079  63.871  54.039   61.95  63.777  62.407  78.249  62.233  82.351  60.653
  86.587  60.306 105.733  55.197 156.141  59.322 160.011  60.124 176.322  61.231
 179.393  58.196 185.608   58.54  189.02  60.103 190.234  61.717 240.526  61.488
  254.24  61.017 255.438  59.822 259.263  59.874 259.773  61.062 269.899   61.63
 282.448  61.724 295.643  61.159 300.408  62.916 303.466   64.84 308.591  64.761
#Mann= 3 , 0 , 0
       0    .033       0       0    .033       0 308.591    .033       0
Bank Sta=0,308.591
XS Rating Curve= 0 ,0
Exp/Cntr=0.3,0.1

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
Type RM Length L Ch R = 1 ,12647.5 ,9.789,9.789,9.789
BEGIN DESCRIPTION:
Topo1  11483.305
END DESCRIPTION:
XS GIS Cut Line= 3
991652.147140933174038.856130668991535.887028495 174117.11867522
991419.626916057174195.381219773
#Sta/Elev= 30
       0  63.514   6.101   63.79   7.781  63.716  13.522  59.906  17.036  59.422
   51.88  58.128  60.024  58.753  75.592  58.833  79.796  57.519   93.27  57.175
  99.587  55.453 110.499  55.471 111.972  54.875 125.707  53.745 137.452  53.908
 146.013  54.727 147.429  55.366  161.63  55.951 170.544   56.51 176.031  55.248
 183.808  54.954 195.338  53.761 212.519  53.537  222.09  54.001 223.284  55.256
 227.712  56.424  251.17  57.085 267.176  57.847 275.217  64.038 280.295  63.649
#Mann= 3 , 0 , 0
       0    .033       0       0    .033       0 280.295    .033       0
Bank Sta=0,280.295
XS Rating Curve= 0 ,0
Exp/Cntr=0.3,0.1

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
Type RM Length L Ch R = 1 ,12461.5 ,9.5,9.5,9.5
BEGIN DESCRIPTION:
Topo1  11669.316
END DESCRIPTION:
XS GIS Cut Line= 3
991536.569668682173885.793880028 991424.97271301173967.822059584
991313.375757337 174049.85023914
#Sta/Elev= 30
       0  62.584   3.963  62.584   5.483  62.566   8.822  59.373   23.75  58.397
  29.071  58.374  34.852  58.585  40.509  59.433  46.266  57.257  64.799  57.257
  78.353  57.551  94.501  58.215 100.443  55.071 101.977  53.707 110.923  52.391
 124.637  52.976 158.176   54.33 180.808  54.248 200.934  55.071 204.225  56.603
 213.375  56.714 225.345  56.504 237.793  56.667 248.365  56.785 256.584  56.901
 261.414  59.722  262.27  59.813 271.685  60.813 273.463  62.568 277.001  62.568
#Mann= 3 , 0 , 0
       0    .033       0       0    .033       0 277.001    .033       0
Bank Sta=0,277.001
XS Rating Curve= 0 ,0
Exp/Cntr=0.3,0.1

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
Type RM Length L Ch R = 1 ,12347.5 ,9.863,9.863,9.863
BEGIN DESCRIPTION:
Topo1  11783.333
END DESCRIPTION:
XS GIS Cut Line= 3
991473.356639698173794.352036127 991357.39719254 173876.09578881
991241.437745382173957.839541492
#Sta/Elev= 27
       0  61.536    4.52   61.51   6.168  61.212   9.329  58.023  25.575  58.095
  34.919  58.397  38.922  56.793  65.416  56.533  86.743  56.836 101.583  57.259
 106.911  55.276  108.28   53.56 117.997  52.194 142.814   52.66 161.704  53.131
 189.454  53.531 203.165  54.655 205.346  55.254 222.923   55.76 227.741  57.638
  236.53  57.731 248.885  57.213 266.114  56.718 274.912  56.594 280.383   60.67
 281.014  60.679  283.75   60.72
#Mann= 3 , 0 , 0
       0    .033       0       0    .033       0  283.75    .033       0
Bank Sta=0,283.75
XS Rating Curve= 0 ,0
Exp/Cntr=0.3,0.1

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
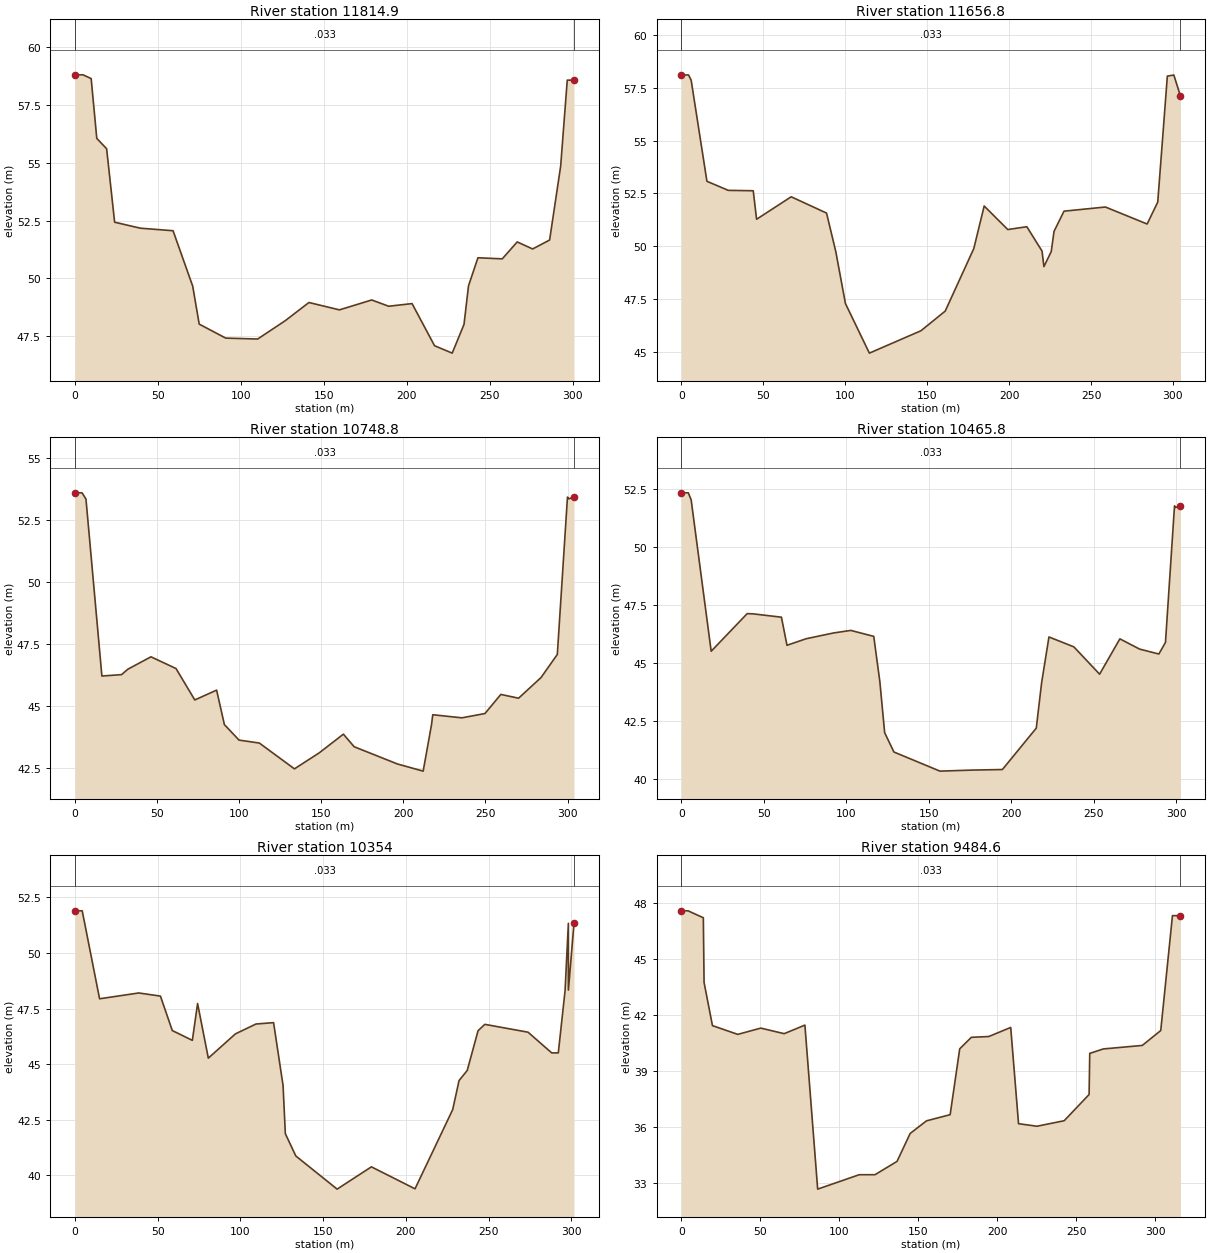
Type RM Length L Ch R = 1 ,11814.9 ,9.881,9.881,9.881
BEGIN DESCRIPTION:
Topo1  12315.971
END DESCRIPTION:
XS GIS Cut Line= 3
991191.551933657173352.103879808991065.762270016173434.579444517
990939.972606374173517.055009225
#Sta/Elev= 30
       0  58.813   4.834  58.813   9.753  58.651  13.137   56.06  19.078  55.611
  23.902  52.428  39.464  52.169  59.121  52.059  70.966  49.659  74.885  48.014
  90.855  47.408 110.133  47.368 126.827  48.166  141.04   48.95 159.419  48.631
 178.918   49.06 189.107  48.788 203.208  48.903 216.775  47.077 227.416  46.757
 234.531  48.003 237.228  49.667 242.914  50.888 257.584  50.841 266.592  51.574
 275.903   51.27 286.132  51.656 292.794  54.856 296.774  58.583 300.833  58.583
#Mann= 3 , 0 , 0
       0    .033       0       0    .033       0 300.833    .033       0
Bank Sta=0,300.833
XS Rating Curve= 0 ,0
Exp/Cntr=0.3,0.1

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
Type RM Length L Ch R = 1 ,11656.8 ,9.978,9.978,9.978
BEGIN DESCRIPTION:
Topo1  12474.084
END DESCRIPTION:
XS GIS Cut Line= 3
991111.669745379 173223.73142703990980.812204608173301.624409216
990849.954663837173379.517391402
#Sta/Elev= 29
       0  58.122    4.33  58.113   5.919  57.869  15.549  53.073  28.592  52.644
  43.803  52.625  45.859  51.274  66.982  52.339  88.555  51.567  94.193  49.743
 100.087  47.278 114.694  44.926 146.153  45.986 160.988  46.919 178.445  49.885
 184.767  51.902 199.173  50.786 210.803   50.92 220.096  49.764 221.216  49.028
 225.693  49.739   227.4  50.698  233.49  51.657 258.772  51.854  284.23  51.048
 290.705  52.087 296.565  58.061 300.539  58.112 304.571  57.116
#Mann= 3 , 0 , 0
       0    .033       0       0    .033       0 304.571    .033       0
Bank Sta=0,304.571
XS Rating Curve= 0 ,0
Exp/Cntr=0.3,0.1

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
Type RM Length L Ch R = 1 ,10748.8 ,9.759,9.759,9.759
BEGIN DESCRIPTION:
Topo1  13382.052
END DESCRIPTION:
XS GIS Cut Line= 3
990606.692924364172463.539886329 990479.84406152172547.246599969
990352.995198675 172630.95331361
#Sta/Elev= 30
       0  53.588   4.321   53.59   6.689  53.337  16.387  46.217  28.372  46.273
  32.187   46.49  46.288   46.99  61.534  46.518  72.971  45.254  86.266  45.649
  91.011  44.261  99.914  43.638 112.293  43.519 133.681   42.48 148.723  43.122
 163.502  43.877 170.038  43.371 196.358  42.678  212.08  42.389 217.156  44.253
 217.931  44.659 235.645  44.534 249.709  44.707 259.393  45.476 270.195  45.324
 283.872  46.155 293.802  47.086 299.977  53.419 300.814   53.35 303.956  53.419
#Mann= 3 , 0 , 0
       0    .033       0       0    .033       0 303.956    .033       0
Bank Sta=0,303.956
XS Rating Curve= 0 ,0
Exp/Cntr=0.3,0.1

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
Type RM Length L Ch R = 1 ,10465.8 ,9.317,9.317,9.317
BEGIN DESCRIPTION:
Topo1  13665.077
END DESCRIPTION:
XS GIS Cut Line= 3
990467.623050253172237.124046258990332.811885616172305.623771231
990198.000720978172374.123496205
#Sta/Elev= 30
       0  52.316   4.153  52.316   5.871  52.018  18.012  45.489   39.84   47.11
    43.3  47.101  60.585  46.957  63.959  45.746  75.615  46.029  92.184  46.277
 102.635  46.387 116.543   46.13 120.251  44.174 123.151  41.981 128.763  41.147
 156.648  40.323 175.848  40.367 194.518  40.392 215.047  42.176 218.293  44.138
 222.733  46.105  237.84  45.677 253.422  44.501 265.716  46.023 277.638  45.583
 289.343   45.37 293.343   45.87 298.828  51.755 299.502  51.686 302.431  51.755
#Mann= 3 , 0 , 0
       0    .033       0       0    .033       0 302.431    .033       0
Bank Sta=0,302.431
XS Rating Curve= 0 ,0
Exp/Cntr=0.3,0.1

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
Type RM Length L Ch R = 1 ,10354   ,9.993,9.993,9.993
BEGIN DESCRIPTION:
Topo1  13776.881
END DESCRIPTION:
XS GIS Cut Line= 3
990426.898670095172146.887498118990287.209151001172203.759261169
990147.519631907 172260.63102422
#Sta/Elev= 30
       0  51.891   4.371  51.891  14.868  47.939  38.558    48.2  51.658  48.059
  58.814  46.512  70.941  46.071  74.111  47.726  80.596  45.272   96.99  46.363
 109.404  46.805 120.044  46.867 125.781  44.041 127.154  41.877 133.506  40.875
 158.459  39.386 179.184  40.387 205.552    39.4 228.325   42.96 232.165  44.263
 237.113  44.719 243.652  46.504 247.745   46.79 273.876  46.437 288.162  45.508
 292.161  45.508 296.253  48.307 298.249  51.328 298.259  48.328 301.645  51.332
#Mann= 3 , 0 , 0
       0    .033       0       0    .033       0 301.645    .033       0
Bank Sta=0,301.645
XS Rating Curve= 0 ,0
Exp/Cntr=0.3,0.1

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
Type RM Length L Ch R = 1 ,9484.6  ,9.4,9.4,9.4
BEGIN DESCRIPTION:
Topo1  14646.277
END DESCRIPTION:
XS GIS Cut Line= 3
990242.613039699171358.958600109990084.763346112171365.961749725
989926.913652524171372.964899341
#Sta/Elev= 30
       0  47.589   4.202  47.589  13.855  47.218  14.321  43.754  19.628  41.446
  35.636  40.976  50.232  41.312  65.047  41.014  78.178  41.473  86.267  32.694
 112.559  33.465 122.559  33.465 136.528  34.179  144.84  35.673 155.191  36.349
 170.159  36.679  176.22  40.203 183.578  40.819  194.64  40.862 208.509  41.347
 213.471  36.196 225.137   36.06 242.373  36.355 258.147  37.758 258.562  39.958
 267.173  40.197  291.84  40.385 303.521  41.182  310.94  47.332 316.009  47.332
#Mann= 3 , 0 , 0
       0    .033       0       0    .033       0 316.009    .033       0
Bank Sta=0,316.009
XS Rating Curve= 0 ,0
Exp/Cntr=0.3,0.1

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
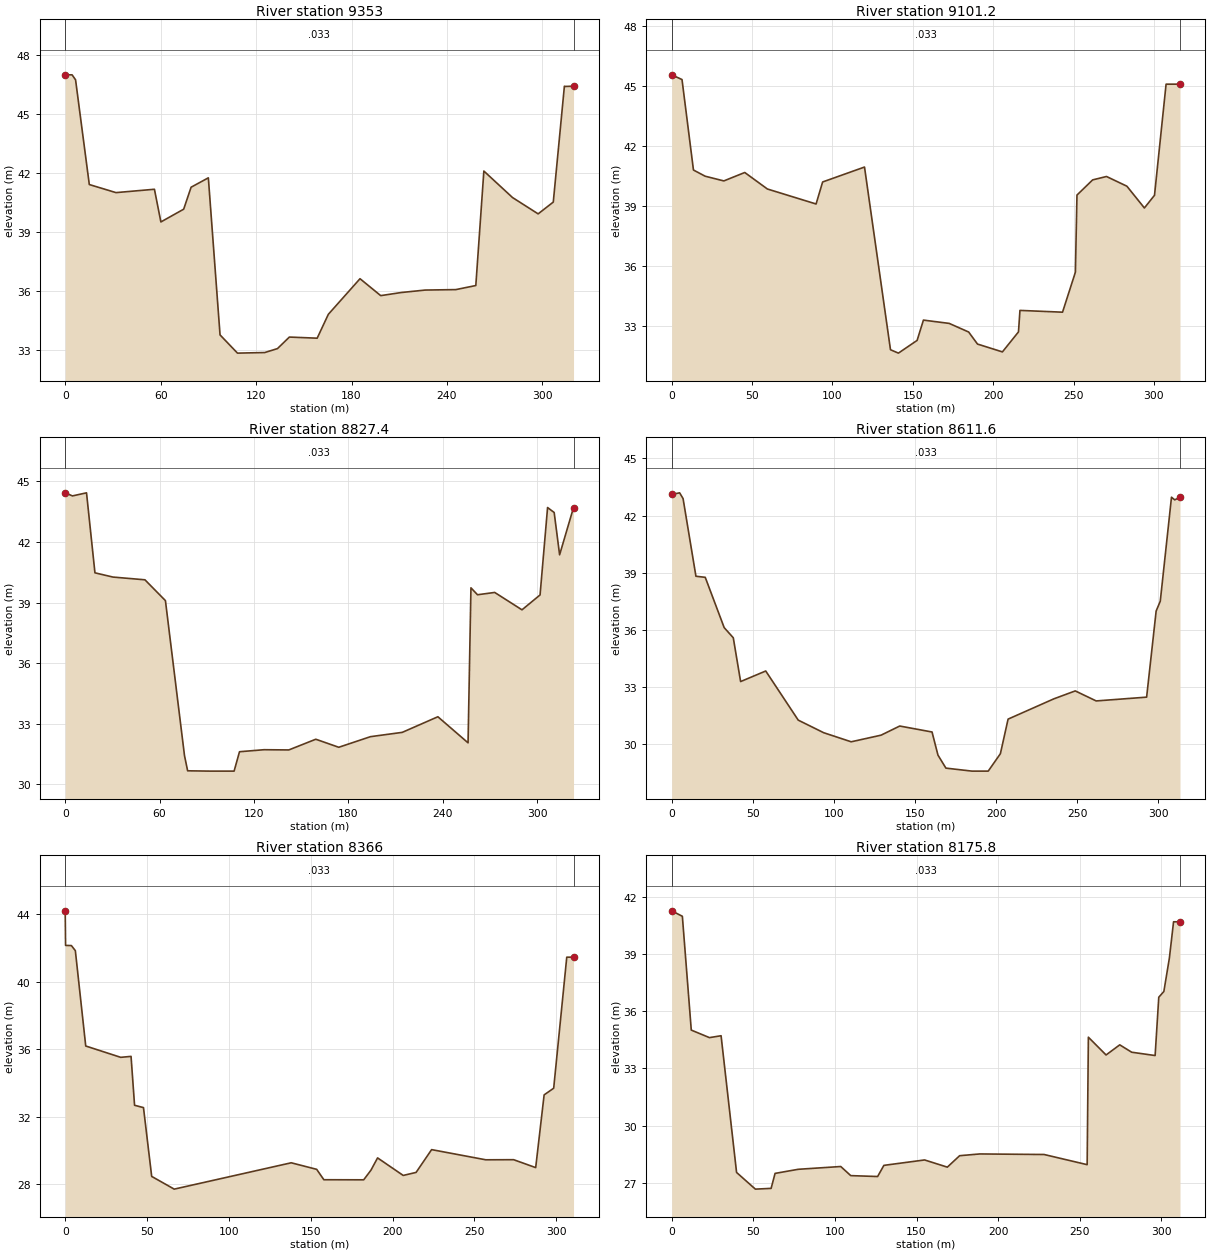
Type RM Length L Ch R = 1 ,9353    ,9.685,9.685,9.685
BEGIN DESCRIPTION:
Topo1  14777.806
END DESCRIPTION:
XS GIS Cut Line= 3
990233.198480981 171237.34916998990073.433937024171235.660629763
989913.669393066171233.972089547
#Sta/Elev= 30
       0   47.01   4.324   47.01   6.511  46.756  15.151  41.422  31.927  41.011
  56.088  41.182  60.146  39.517  74.476  40.167  79.143  41.286  89.985  41.764
  97.333  33.764 108.299  32.836 125.433  32.866 133.434  33.066 140.916  33.654
   158.4  33.597 165.409  34.812 185.323  36.626 198.343  35.764  211.17  35.922
 226.281  36.048 245.555  36.071 258.121  36.279 263.179  42.109 281.197   40.76
   297.3  39.928 306.819  40.529 313.804   46.43 314.483  46.419 319.546   46.43
#Mann= 3 , 0 , 0
       0    .033       0       0    .033       0 319.546    .033       0
Bank Sta=0,319.546
XS Rating Curve= 0 ,0
Exp/Cntr=0.3,0.1

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
Type RM Length L Ch R = 1 ,9101.2  ,9.779,9.779,9.779
BEGIN DESCRIPTION:
Topo1  15029.633
END DESCRIPTION:
XS GIS Cut Line= 3
990263.809135583171011.718153773990107.754766247170986.396012928
989951.700396912170961.073872084
#Sta/Elev= 30
       0  45.538    6.43  45.302   13.55  40.781  20.816  40.472  32.448  40.236
  45.462  40.657  59.518  39.833  89.831  39.083  93.899  40.183 119.948  40.929
 136.108    31.8 141.029   31.63 152.674  32.266 156.594   33.28 172.615  33.116
 184.727  32.685 190.233  32.083 205.726  31.691 215.726  32.691 216.638  33.765
 243.129  33.676 251.129  35.676 252.107  39.529 261.853  40.287 270.474  40.457
 283.158  39.972 294.042  38.884 300.337  39.519 307.534  45.071  316.19  45.071
#Mann= 3 , 0 , 0
       0    .033       0       0    .033       0  316.19    .033       0
Bank Sta=0,316.19
XS Rating Curve= 0 ,0
Exp/Cntr=0.3,0.1

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
Type RM Length L Ch R = 1 ,8827.4  ,9.809,9.809,9.809
BEGIN DESCRIPTION:
Topo1  15303.406
END DESCRIPTION:
XS GIS Cut Line= 3
990307.256950325170743.749481804990147.993835383170716.425891392
989988.730720441170689.102300979
#Sta/Elev= 30
       0  44.439   4.621  44.286  13.552  44.439  18.909  40.478  30.366  40.268
  50.685  40.133  63.717  39.102   75.85  31.423  77.843  30.676  92.374   30.66
 107.374   30.66 110.816   31.62 126.398   31.72  142.16  31.709 159.321  32.239
 173.927  31.841 194.073  32.366 214.282  32.579 236.937  33.352 256.119  32.061
 257.962  39.735 262.126  39.392 273.062  39.507 290.407  38.646   301.9  39.383
 306.679  43.711 308.187  43.622 310.873  43.464 314.332  41.371 323.179  43.711
#Mann= 3 , 0 , 0
       0    .033       0       0    .033       0 323.179    .033       0
Bank Sta=0,323.179
XS Rating Curve= 0 ,0
Exp/Cntr=0.3,0.1

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
Type RM Length L Ch R = 1 ,8611.6  ,9.824,9.824,9.824
BEGIN DESCRIPTION:
Topo1  15519.276
END DESCRIPTION:
XS GIS Cut Line= 3
990351.754997243170541.819968192990199.062537765 170506.77069486
990046.370078288170471.721421528
#Sta/Elev= 30
       0   43.11   4.901  43.197    7.02  42.897  14.954   38.82  20.695  38.763
  32.369  36.123  37.978  35.591  42.495  33.293  57.976  33.848  78.014   31.27
   93.69   30.61 110.652  30.133 129.052   30.48 140.587   30.96 160.489  30.647
 164.131  29.436  169.03  28.752 185.115  28.594 195.115  28.594 202.617  29.508
 207.368  31.323 235.664   32.39 248.768  32.803 261.662  32.277 292.758  32.476
 298.627  36.996 301.168   37.51 308.081  42.966 310.079  42.828 313.326  42.966
#Mann= 3 , 0 , 0
       0    .033       0       0    .033       0 313.326    .033       0
Bank Sta=0,313.326
XS Rating Curve= 0 ,0
Exp/Cntr=0.3,0.1

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
Type RM Length L Ch R = 1 ,8366    ,9.51,9.51,9.51
BEGIN DESCRIPTION:
Topo1  15764.823
END DESCRIPTION:
XS GIS Cut Line= 3
990396.431169592170279.736823892990241.813103973170265.551024508
990087.195038355170251.365225125
#Sta/Elev= 27
       0  44.194    .225  42.146   3.773  42.138   6.192  41.837  12.538  36.193
  33.911  35.522  40.225  35.578  42.367  32.685  47.818  32.546  52.829  28.474
  66.597  27.721 138.078   29.28 153.631  28.892 158.005  28.277 182.344  28.272
 186.759  28.839 190.829  29.569 206.483  28.531 214.346   28.71 223.836  30.059
  256.91  29.457  273.95  29.463 287.418  28.995 292.572    33.3 298.412  33.694
 306.397   41.45 310.534   41.45
#Mann= 3 , 0 , 0
       0    .033       0       0    .033       0 310.534    .033       0
Bank Sta=0,310.534
XS Rating Curve= 0 ,0
Exp/Cntr=0.3,0.1

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
Type RM Length L Ch R = 1 ,8175.8  ,9.884,9.884,9.884
BEGIN DESCRIPTION:
Topo1  15955.086
END DESCRIPTION:
XS GIS Cut Line= 3
990412.017278141170101.667586265990258.351529529170076.593881883
990104.685780918170051.520177502
#Sta/Elev= 30
       0  41.267    6.55  40.981  12.007  35.012  23.142  34.617  30.265  34.716
  39.757  27.546  51.268  26.671  60.916   26.71  63.337  27.496  77.541  27.711
 103.577  27.857 109.706  27.379 126.164  27.332 129.995  27.917 154.952  28.201
 168.865  27.824 176.403  28.424  188.73  28.516 228.147  28.487  254.52  27.954
 255.264  34.639 266.106  33.707 274.485  34.238 281.812  33.851 296.158  33.677
 298.395  36.735 301.515  37.038 304.901  38.793 307.453  40.692 311.395  40.692
#Mann= 3 , 0 , 0
       0    .033       0       0    .033       0 311.395    .033       0
Bank Sta=0,311.395
XS Rating Curve= 0 ,0
Exp/Cntr=0.3,0.1

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