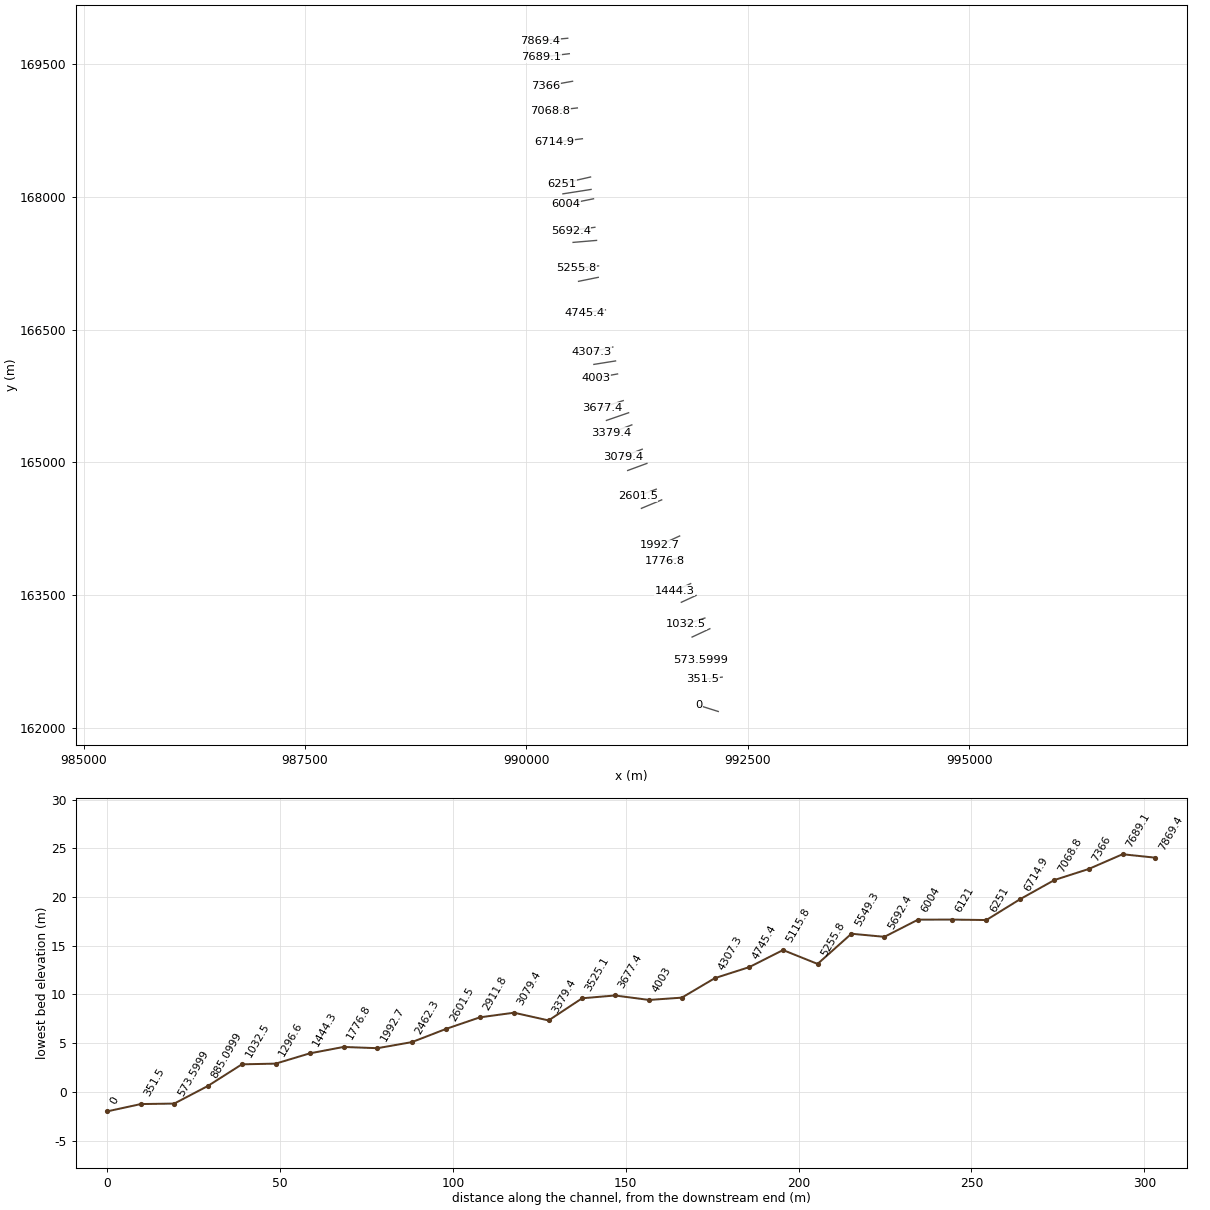
HEC-RAS study Var.prj: Var

--- Var.g01 (geometry) --- (continued)

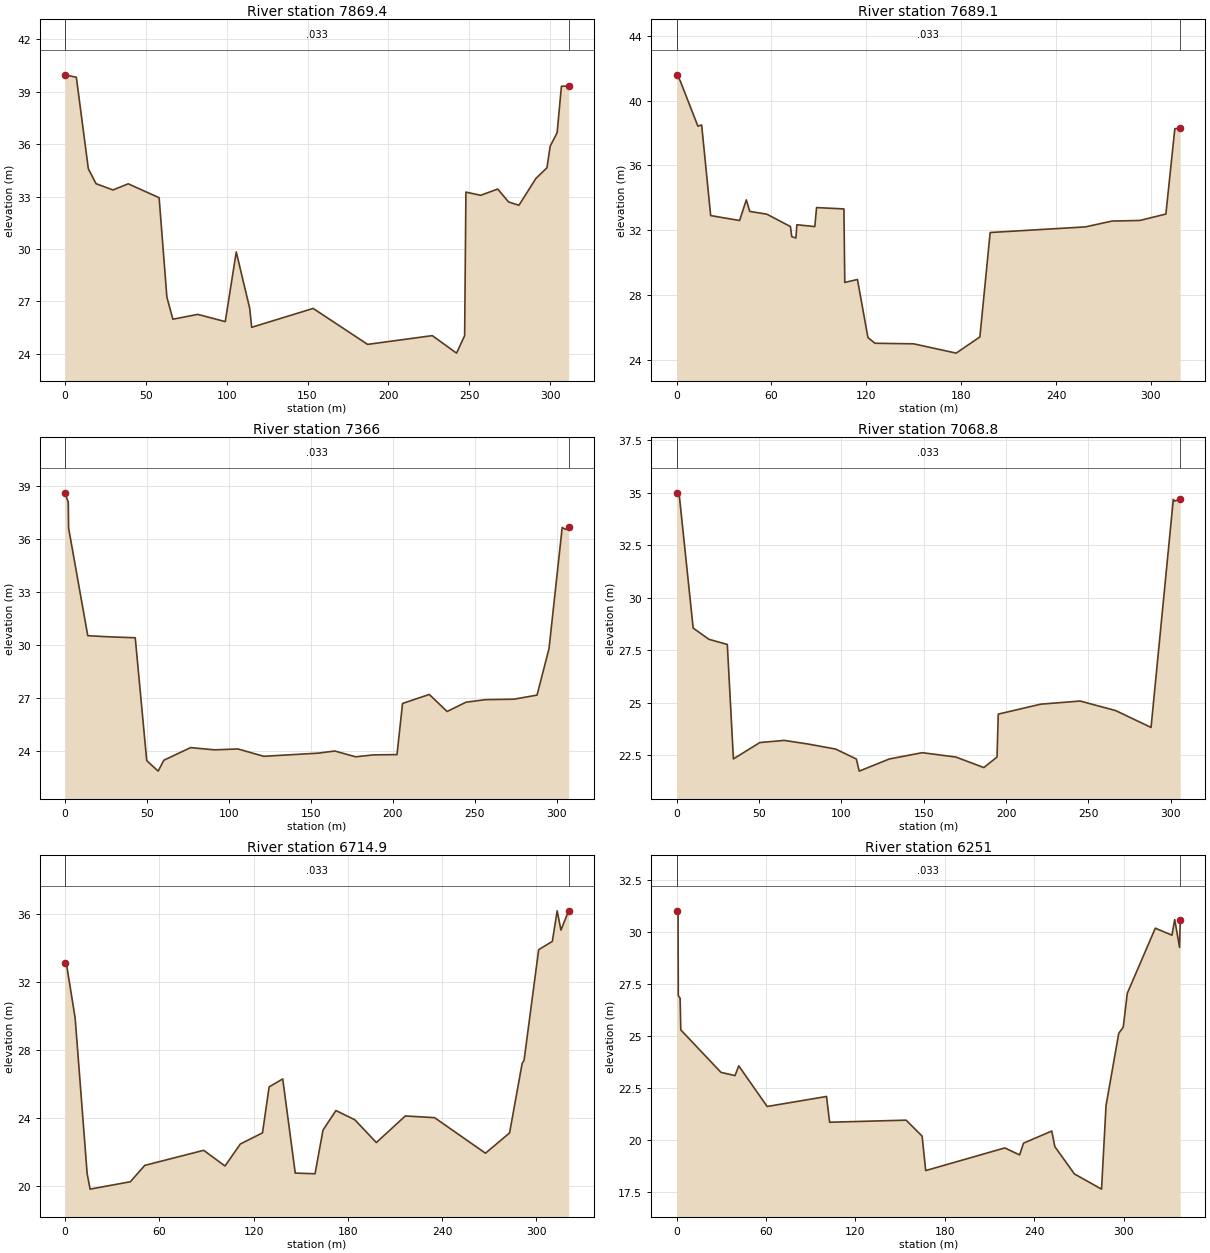
Type RM Length L Ch R = 1 ,7869.4  ,9.489,9.489,9.489
BEGIN DESCRIPTION:
Topo1  16261.432
END DESCRIPTION:
XS GIS Cut Line= 3
 990466.94529806169790.066751613990311.912970224169775.566535976
990156.880642387 169761.06632034
#Sta/Elev= 30
       0  39.957    7.03  39.818  14.446  34.586  19.212  33.732  29.689  33.374
  39.105  33.726  58.212  32.931  63.008  27.249  66.725  25.984    82.1   26.26
  99.109  25.847 105.906  29.831 114.212  26.607 115.444  25.522 153.442    26.6
 187.117  24.545 227.117  25.045 242.116  24.045 247.117  25.045 247.903  33.253
 257.016  33.068 267.572  33.426 274.296  32.687 280.696    32.5 291.203  34.036
 298.013  34.642 299.995  35.874 304.301  36.649 306.963  39.307 311.417  39.307
#Mann= 3 , 0 , 0
       0    .033       0       0    .033       0 311.417    .033       0
Bank Sta=0,311.417
XS Rating Curve= 0 ,0
Exp/Cntr=0.3,0.1

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
Type RM Length L Ch R = 1 ,7689.1  ,9.791,9.791,9.791
BEGIN DESCRIPTION:
Topo1  16441.709
END DESCRIPTION:
XS GIS Cut Line= 3
990484.423518859169615.547822019990326.359711241169596.081540048
990168.295903623169576.615258077
#Sta/Elev= 30
       0  41.597   2.156  41.263  13.482  38.428  15.862  38.494  21.579  32.898
  39.859  32.595  44.106  33.871  46.277  33.157   57.13  32.984  72.018  32.221
  72.848  31.595   75.47  31.514  76.081  32.333  87.415  32.219  88.539  33.394
 105.843   33.31 106.371  28.766 114.403   28.95 121.015  25.362 125.484  25.009
 149.959  24.974 176.818  24.399 191.818  25.399 198.316  31.852 258.479  32.199
 275.416   32.56 292.942  32.597 309.449  32.994 315.097  38.269 318.515   38.29
#Mann= 3 , 0 , 0
       0    .033       0       0    .033       0 318.515    .033       0
Bank Sta=0,318.515
XS Rating Curve= 0 ,0
Exp/Cntr=0.3,0.1

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
Type RM Length L Ch R = 1 ,7366    ,9.907,9.907,9.907
BEGIN DESCRIPTION:
Topo1  16764.810
END DESCRIPTION:
XS GIS Cut Line= 3
990521.420373393169304.133539283990370.148636744169277.016930581
990218.876900096169249.900321878
#Sta/Elev= 29
       0  38.639   2.006  38.108   2.228  36.639  13.909  30.551  28.284  30.481
  42.882  30.435  49.893   23.48  56.872  22.884  60.333  23.501  76.686  24.216
  91.108  24.089 105.578  24.139 121.335  23.723 154.588  23.902 164.648  24.023
 177.377  23.695 188.322  23.804 202.622  23.819 206.004  26.714 222.324  27.225
 233.211  26.259 244.705  26.786  256.71  26.931 274.012  26.956 288.076  27.188
 295.393  29.818 303.433  36.679 305.446  36.568 307.365  36.679
#Mann= 3 , 0 , 0
       0    .033       0       0    .033       0 307.365    .033       0
Bank Sta=0,307.365
XS Rating Curve= 0 ,0
Exp/Cntr=0.3,0.1

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
Type RM Length L Ch R = 1 ,7068.8  ,9.831,9.831,9.831
BEGIN DESCRIPTION:
Topo1  17062.070
END DESCRIPTION:
XS GIS Cut Line= 3
990575.488783044169002.888242816990423.606193912168985.741157838
 990271.72360478 168968.59407286
#Sta/Elev= 25
       0  34.987     1.5   34.98  10.078  28.555  19.637  28.021    30.8  27.776
  34.506  22.334  50.533  23.111  65.351  23.213  79.575  23.044  96.533  22.802
 109.105  22.329 110.855  21.752 129.104  22.329 149.104  22.629 169.505  22.422
 186.505  21.922 194.505  22.422 195.246  24.463 221.026  24.936 244.915  25.085
 266.419  24.634 287.984   23.83  301.49  34.675 302.287  34.595 305.694  34.675
#Mann= 3 , 0 , 0
       0    .033       0       0    .033       0 305.694    .033       0
Bank Sta=0,305.694
XS Rating Curve= 0 ,0
Exp/Cntr=0.3,0.1

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
Type RM Length L Ch R = 1 ,6714.9  ,9.87,9.87,9.87
BEGIN DESCRIPTION:
Topo1  17415.908
END DESCRIPTION:
XS GIS Cut Line= 3
990632.517159576168655.046346953990473.433696399168635.663036015
990314.350233221168616.279725077
#Sta/Elev= 30
       0  33.072    1.14  32.936   6.479   29.86  14.101  20.726  15.999  19.805
  41.594  20.239  50.759    21.2   88.27  22.087 101.838  21.165 111.606   22.46
 125.691   23.11 129.924  25.816 138.575  26.283 146.545  20.747 159.135   20.71
 164.207  23.274 172.427  24.424 184.447  23.883 198.152  22.543 216.594  24.107
 235.223  24.005 267.595  21.917 282.924  23.107 290.935  27.196 292.164  27.382
 301.449  33.882 310.142  34.369 313.227  36.165 315.621  35.031 320.519  36.165
#Mann= 3 , 0 , 0
       0    .033       0       0    .033       0 320.519    .033       0
Bank Sta=0,320.519
XS Rating Curve= 0 ,0
Exp/Cntr=0.3,0.1

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
Type RM Length L Ch R = 1 ,6251    ,10,10,10
BEGIN DESCRIPTION:
Topo1  17879.832
END DESCRIPTION:
XS GIS Cut Line= 3
990724.685501335168222.996865132         990560.168185.515113699
990395.314498665168148.033362266
#Sta/Elev= 30
       0  30.967     .99  30.997   1.162  26.931   2.384    26.8   2.839  25.282
  29.777  23.245  39.218  23.089  41.689  23.557  60.772  21.607 100.576  22.087
 102.628  20.851 153.941  20.951 164.691  20.184 167.087  18.531 220.155  19.618
 230.071  19.282 232.692  19.847 251.653  20.429 253.688  19.681  266.84  18.369
 285.027  17.641 288.027  21.651  296.58  25.121 299.591  25.416 302.282   27.04
 321.085  30.164 332.253  29.827 334.104  30.578 337.369  29.238 337.793  30.578
#Mann= 3 , 0 , 0
       0    .033       0       0    .033       0 337.793    .033       0
Bank Sta=0,337.793
XS Rating Curve= 0 ,0
Exp/Cntr=0.3,0.1

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
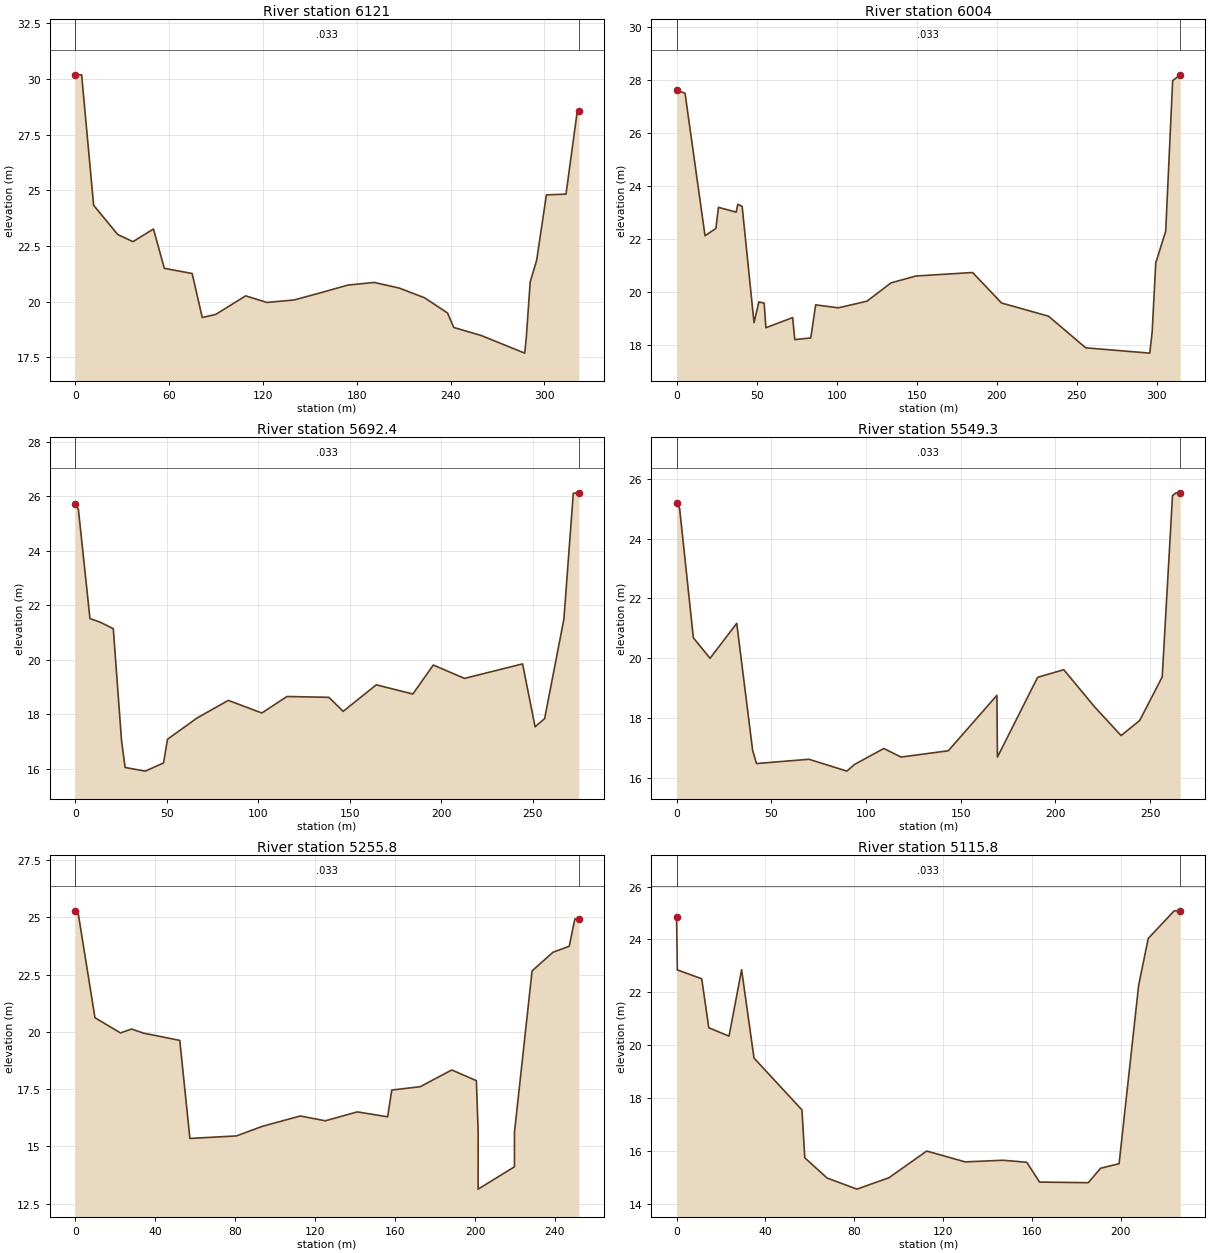
Type RM Length L Ch R = 1 ,6121    ,9.75,9.75,9.75
BEGIN DESCRIPTION:
Topo1  18009.832
END DESCRIPTION:
XS GIS Cut Line= 3
990730.847784254168082.464746912990571.784760292168057.591909197
 990412.72173633168032.719071482
#Sta/Elev= 30
       0  30.193   4.094  30.193  11.769  24.332  27.173  23.018  36.895  22.698
  50.024  23.265  56.973  21.499  74.749  21.267  81.222  19.289  89.842  19.429
 108.942  20.262 122.535  19.966 139.853  20.076 157.283  20.409 174.371  20.747
 191.167  20.865 207.135  20.612 223.337  20.175 238.035  19.491 241.996  18.842
 259.489  18.482 287.365  17.689 288.365  18.389 290.865  20.889 294.995  21.864
  301.22  24.798 313.755  24.834 318.239  27.155 320.925  28.546 321.991  28.546
#Mann= 3 , 0 , 0
       0    .033       0       0    .033       0 321.991    .033       0
Bank Sta=0,321.991
XS Rating Curve= 0 ,0
Exp/Cntr=0.3,0.1

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
Type RM Length L Ch R = 1 ,6004    ,9.738,9.738,9.738
BEGIN DESCRIPTION:
Topo1  18126.879
END DESCRIPTION:
XS GIS Cut Line= 3
990758.235520742 167976.74340057990604.023734137167945.798259835
990449.811947533167914.853119099
#Sta/Elev= 30
       0  27.614   5.302  27.502  17.778  22.116  24.551  22.393  26.174  23.189
  37.244  23.008  38.249  23.308  40.959  23.225  48.377  18.834  51.416  19.617
  54.726  19.569  55.786  18.641  72.493  19.023  73.859  18.193  83.825  18.254
  86.873  19.505 101.039  19.392 118.949  19.645  133.92  20.335 149.514  20.595
   184.9  20.727 202.976  19.575 232.329  19.076 255.547  17.881 295.548  17.681
 297.047  18.481 299.278  21.087 305.497  22.289 309.842  27.977 314.571  28.197
#Mann= 3 , 0 , 0
       0    .033       0       0    .033       0 314.571    .033       0
Bank Sta=0,314.571
XS Rating Curve= 0 ,0
Exp/Cntr=0.3,0.1

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
Type RM Length L Ch R = 1 ,5692.4  ,9.54,9.54,9.54
BEGIN DESCRIPTION:
Topo1  18438.408
END DESCRIPTION:
XS GIS Cut Line= 3
990773.492860586167654.989384291990637.230308364167636.258560968
990500.967756142167617.527737644
#Sta/Elev= 28
       0  25.733   1.731   25.52   8.049  21.516  13.726  21.379  20.797  21.143
  25.287  17.046  27.247  16.051  38.244  15.917  48.243  16.217  50.397  17.086
  66.605  17.869  83.608  18.513 101.918   18.05 115.671  18.655 138.543  18.625
  146.34   18.11 164.436  19.084 184.391  18.746 195.579  19.809 212.639  19.319
 244.327  19.852 251.164  17.543 256.385  17.844 266.896  21.495  272.03  26.113
 273.229  26.121 274.151  26.128 275.087  26.128
#Mann= 3 , 0 , 0
       0    .033       0       0    .033       0 275.087    .033       0
Bank Sta=0,275.087
XS Rating Curve= 0 ,0
Exp/Cntr=0.3,0.1

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
Type RM Length L Ch R = 1 ,5549.3  ,9.783,9.783,9.783
BEGIN DESCRIPTION:
Topo1  18581.587
END DESCRIPTION:
XS GIS Cut Line= 3
990792.468930847167506.780291646         990660.167495.570365365
990527.531069153167484.360439084
#Sta/Elev= 25
       0  25.181   1.621  25.002    8.87  20.688  17.667  20.003  31.774  21.171
  40.153  16.932  42.202  16.489  69.897  16.632  89.897  16.236  93.942  16.459
 109.415  16.992 118.478  16.706 143.455  16.916 169.108  18.767 169.385  16.705
 190.603  19.368 204.413  19.622 220.693   18.38 234.674  17.423 244.489  17.927
 256.375  19.381 261.806  25.434  262.52  25.469 263.682  25.527 265.884  25.527
#Mann= 3 , 0 , 0
       0    .033       0       0    .033       0 265.884    .033       0
Bank Sta=0,265.884
XS Rating Curve= 0 ,0
Exp/Cntr=0.3,0.1

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
Type RM Length L Ch R = 1 ,5255.8  ,10,10,10
BEGIN DESCRIPTION:
Topo1  18875.003
END DESCRIPTION:
XS GIS Cut Line= 3
990815.260271711167218.953474125         990690.167205.484140513
990564.739728289167192.014806901
#Sta/Elev= 28
       0  25.286   1.578  25.129   9.886  20.619  22.633  19.955  28.206  20.126
  34.146  19.946  52.307  19.629  57.363  15.349  80.644  15.459  93.714  15.881
 112.602  16.329  125.09  16.119 141.098  16.508 156.277  16.294 158.358  17.461
 172.643  17.609 188.353  18.339 200.674  17.872 201.564  15.636 201.574  13.136
 219.718  14.111 219.728  15.611 228.545  22.665 229.347  22.727 239.002  23.477
 247.125  23.738 249.947   24.93 251.964   24.93
#Mann= 3 , 0 , 0
       0    .033       0       0    .033       0 251.964    .033       0
Bank Sta=0,251.964
XS Rating Curve= 0 ,0
Exp/Cntr=0.3,0.1

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
Type RM Length L Ch R = 1 ,5115.8  ,9.747,9.747,9.747
BEGIN DESCRIPTION:
Topo1  19015.003
END DESCRIPTION:
XS GIS Cut Line= 3
990811.550943751167089.596496318990700.394233426167067.084927483
990589.237523102167044.573358649
#Sta/Elev= 25
       0  24.857    .346   22.85  11.335  22.512  14.516  20.661  23.626  20.343
  29.296  22.854   34.88  19.514  56.466  17.555  57.746  15.744  67.781  14.979
  81.223  14.559  95.616  14.988 112.652  15.999 129.981  15.589 147.072  15.651
  157.72  15.574 163.488  14.826 185.413  14.802 190.974  15.349 199.295   15.52
 208.098  22.263 208.695  22.508 212.411  24.037 224.115  25.082 226.826  25.082
#Mann= 3 , 0 , 0
       0    .033       0       0    .033       0 226.826    .033       0
Bank Sta=0,226.826
XS Rating Curve= 0 ,0
Exp/Cntr=0.3,0.1

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
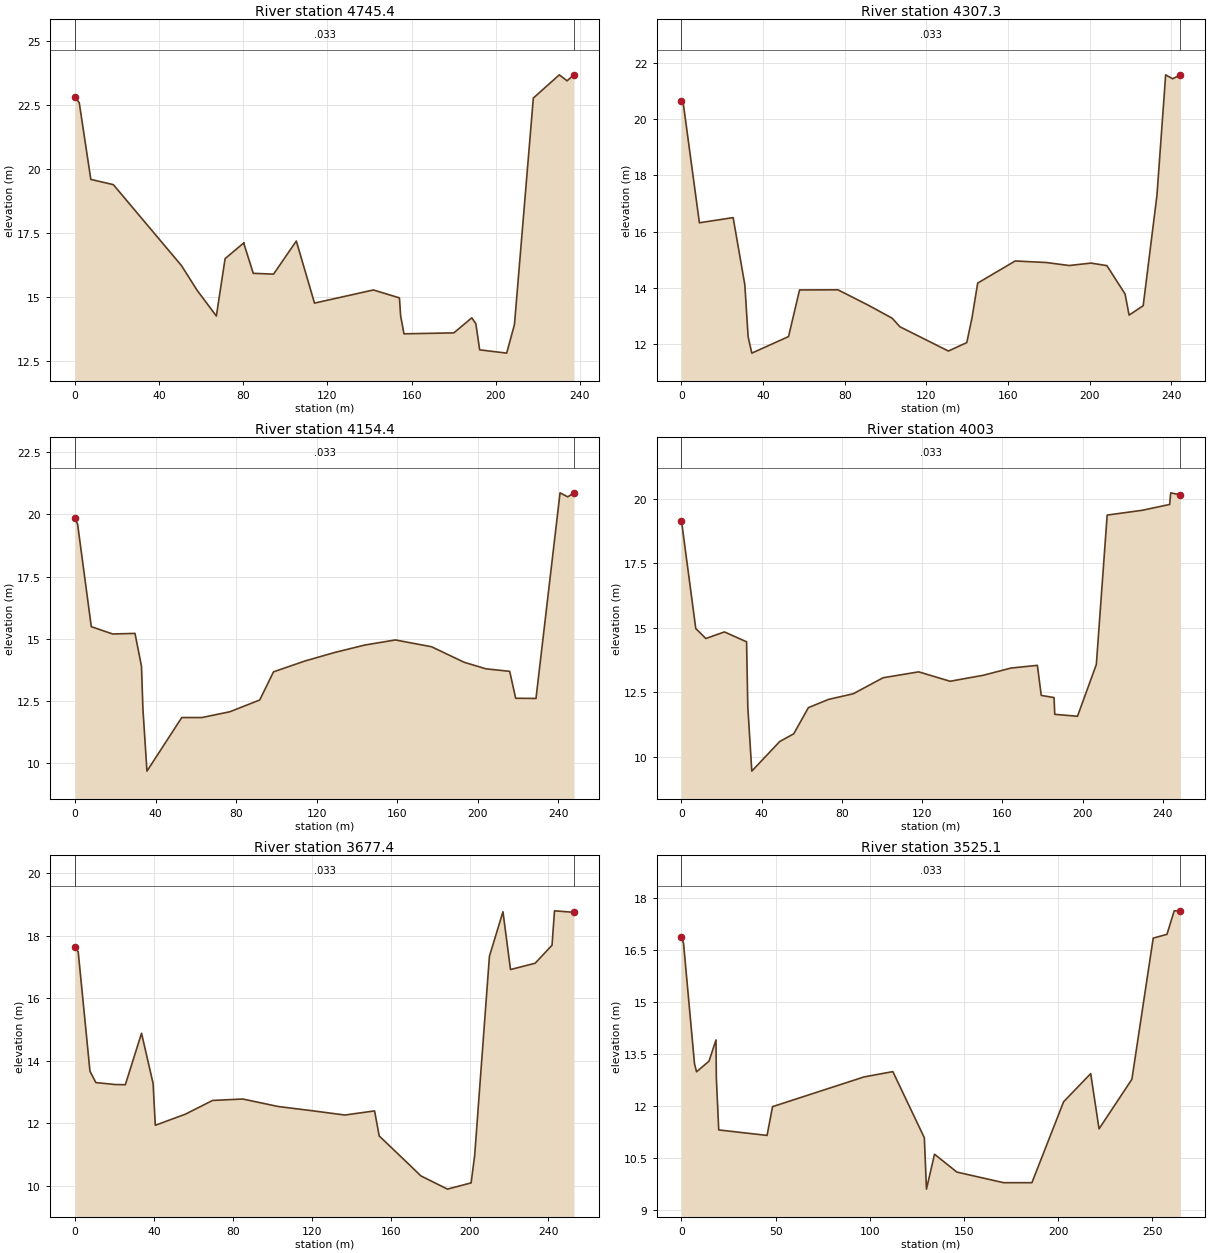
Type RM Length L Ch R = 1 ,4745.4  ,9.957,9.957,9.957
BEGIN DESCRIPTION:
Topo1  19385.424
END DESCRIPTION:
XS GIS Cut Line= 3
990892.691974156166722.241815418990775.245568948 166705.90380184
990657.799163739166689.565788262
#Sta/Elev= 28
       0  22.801   2.021  22.588   7.526  19.592  18.228  19.387  50.602  16.227
  58.116  15.253  67.185  14.258  71.339  16.498   80.34  17.121  80.342  17.064
  84.733  15.924   94.38  15.894 105.186  17.186 113.834  14.762 141.814  15.275
  154.19  14.966 154.773   14.26 156.354  13.563 180.049  13.599 188.581  14.187
 190.516  13.956 192.324  12.937 205.167  12.809 208.856  13.925 217.824  22.767
 230.173  23.675 233.867  23.442 237.154  23.675
#Mann= 3 , 0 , 0
       0    .033       0       0    .033       0 237.154    .033       0
Bank Sta=0,237.154
XS Rating Curve= 0 ,0
Exp/Cntr=0.3,0.1

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
Type RM Length L Ch R = 1 ,4307.3  ,9.556,9.556,9.556
BEGIN DESCRIPTION:
Topo1  19823.523
END DESCRIPTION:
XS GIS Cut Line= 3
990976.113466886166302.740047761990856.766394782166276.168026093
990737.419322677166249.596004425
#Sta/Elev= 30
       0  20.627    .981  20.504   8.789   16.31  25.329  16.494  31.055  14.107
  32.669   12.26  34.478  11.678  52.476  12.266  57.875  13.923  76.694  13.928
  91.649  13.378 103.277  12.918 107.037  12.615 130.822  11.752 139.822  12.052
 142.409  12.943 145.166  14.167 163.564  14.953 178.968  14.897 189.978  14.791
 200.702  14.877 208.487  14.788 217.393   13.78 219.367  13.029 226.275  13.364
 233.018  17.286 237.282  21.568 238.139  21.533 240.694  21.428 244.538  21.568
#Mann= 3 , 0 , 0
       0    .033       0       0    .033       0 244.538    .033       0
Bank Sta=0,244.538
XS Rating Curve= 0 ,0
Exp/Cntr=0.3,0.1

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
Type RM Length L Ch R = 1 ,4154.4  ,9.462,9.462,9.462
BEGIN DESCRIPTION:
Topo1  19976.494
END DESCRIPTION:
XS GIS Cut Line= 3
991006.933572237166145.393354767990884.550639928166125.870200543
990762.167707618 166106.34704632
#Sta/Elev= 27
       0  19.862   1.321  19.595   8.099  15.485  18.723   15.19  29.802  15.214
  33.023  13.894  33.746  12.172  35.747   9.672  53.033  11.828  63.032  11.828
  76.915  12.061  91.754  12.534  98.609  13.667 114.175  14.102 128.791  14.442
 143.935  14.745 159.154   14.95 177.114  14.676 193.299  14.052 204.107  13.789
 215.922  13.687   218.9  12.603 228.982  12.597 240.933   20.87 241.598  20.842
 244.756  20.708  247.86   20.87
#Mann= 3 , 0 , 0
       0    .033       0       0    .033       0  247.86    .033       0
Bank Sta=0,247.86
XS Rating Curve= 0 ,0
Exp/Cntr=0.3,0.1

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
Type RM Length L Ch R = 1 ,4003    ,9.867,9.867,9.867
BEGIN DESCRIPTION:
Topo1  20127.821
END DESCRIPTION:
XS GIS Cut Line= 3
991029.596713896165998.505554462990907.229763572165976.261103333
990784.862813247165954.016652203
#Sta/Elev= 29
       0  19.148   7.138  14.964  12.158  14.577  21.424  14.832  32.459  14.449
  33.068  11.935  35.069   9.435  48.956  10.581  55.957  10.881  63.285  11.897
  73.374  12.217   85.63  12.434 100.538  13.056 118.256  13.284  133.92  12.919
 150.544  13.153 164.306  13.432 177.412  13.536 179.361   12.37 185.727  12.286
 186.083  11.637 197.425  11.562 206.809  13.569 212.212  19.362  212.88  19.369
 229.686  19.548 243.357  19.774 243.891  20.225 248.744  20.142
#Mann= 3 , 0 , 0
       0    .033       0       0    .033       0 248.744    .033       0
Bank Sta=0,248.744
XS Rating Curve= 0 ,0
Exp/Cntr=0.3,0.1

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
Type RM Length L Ch R = 1 ,3677.4  ,9.519,9.519,9.519
BEGIN DESCRIPTION:
Topo1  20453.482
END DESCRIPTION:
XS GIS Cut Line= 3
991093.878387674 165697.34334008990973.567642166 165658.34216828
990853.256896657 165619.34099648
#Sta/Elev= 30
       0   17.63    1.63  17.486   7.591  13.665  10.591  13.302  20.407   13.24
  25.519  13.234  33.731  14.879  39.595  13.274  40.716  11.936  55.976  12.292
  69.748  12.731  85.088  12.776 102.879  12.538 120.325  12.401 136.774  12.264
 151.858  12.396 154.212  11.595  169.43  10.678 175.325  10.318 188.812   9.894
 200.812  10.094 202.619  10.984 210.083  17.343 214.729  18.307 216.941  18.766
 220.759  16.918 233.266   17.12 241.813  17.696 243.067  18.796 252.948  18.748
#Mann= 3 , 0 , 0
       0    .033       0       0    .033       0 252.948    .033       0
Bank Sta=0,252.948
XS Rating Curve= 0 ,0
Exp/Cntr=0.3,0.1

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
Type RM Length L Ch R = 1 ,3525.1  ,9.713,9.713,9.713
BEGIN DESCRIPTION:
Topo1  20605.798
END DESCRIPTION:
XS GIS Cut Line= 3
 991154.59389192165560.225506937 991029.45801256165516.896956039
990904.322133201165473.568405142
#Sta/Elev= 26
       0  16.873     1.1  16.706   6.931  13.225   8.005  12.994  14.631  13.302
  18.333  13.914  18.518   12.82  19.786  11.316  45.432  11.158  48.346  11.988
  96.872  12.846 112.192      13 128.916   11.09 130.039   9.607 134.312  10.615
 146.194  10.099 170.973   9.793 186.009   9.793 202.839   12.13 217.208  12.942
  221.64  11.347  239.07  12.779 250.385  16.854 257.677  16.963 261.538  17.642
 264.849  17.642
#Mann= 3 , 0 , 0
       0    .033       0       0    .033       0 264.849    .033       0
Bank Sta=0,264.849
XS Rating Curve= 0 ,0
Exp/Cntr=0.3,0.1

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
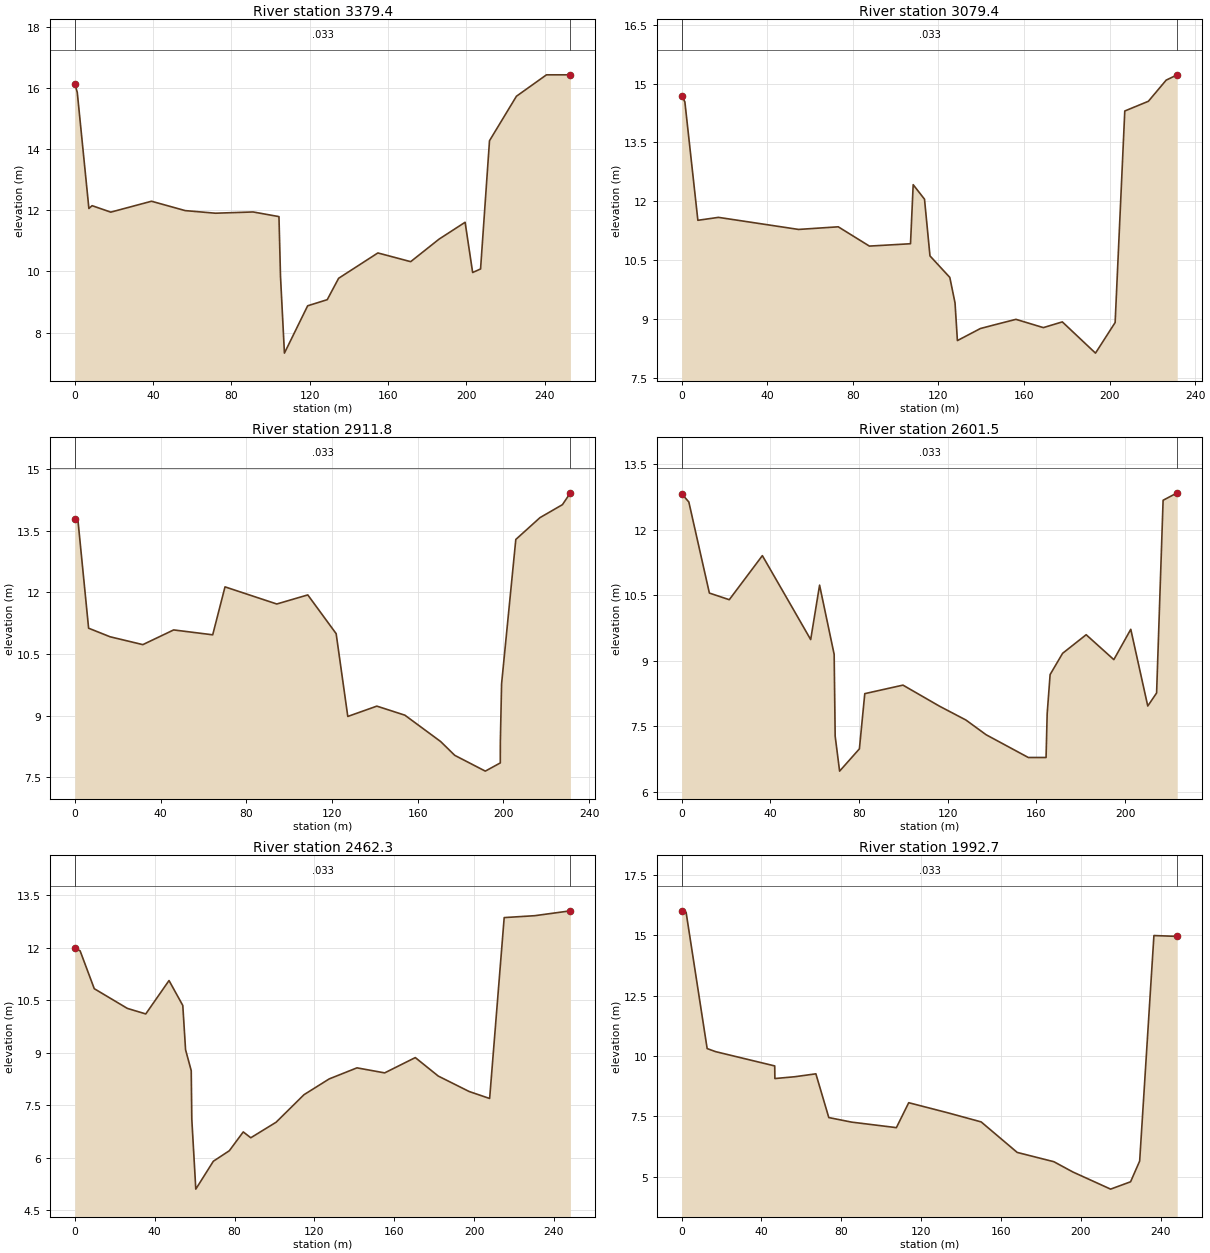
Type RM Length L Ch R = 1 ,3379.4  ,10,10,10
BEGIN DESCRIPTION:
Topo1  20751.400
END DESCRIPTION:
XS GIS Cut Line= 3
991190.996770205165423.202172743991072.822976849165377.942557878
990954.649183493165332.682943013
#Sta/Elev= 26
       0  16.126   1.248  15.851   7.187  12.056   8.828  12.148  18.357  11.937
  39.155  12.293   56.38  11.987  71.823  11.902  91.025  11.943 104.248  11.791
 105.041   9.831 107.041   7.331 118.898   8.877 128.899   9.077  134.72   9.776
 154.758  10.604 171.515  10.319 186.005  11.055 199.309  11.606 203.159   9.965
 207.201  10.081 211.767   14.27 213.515  14.455 225.515  15.723  240.86  16.423
 253.088  16.423
#Mann= 3 , 0 , 0
       0    .033       0       0    .033       0 253.088    .033       0
Bank Sta=0,253.088
XS Rating Curve= 0 ,0
Exp/Cntr=0.3,0.1

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
Type RM Length L Ch R = 1 ,3079.4  ,9.859,9.859,9.859
BEGIN DESCRIPTION:
Topo1  21051.457
END DESCRIPTION:
XS GIS Cut Line= 3
991308.370233497165148.703691863991200.281739109165107.098434851
991092.193244722165065.493177838
#Sta/Elev= 26
       0  14.694     1.5  14.536   7.582  11.513  17.213  11.588  54.644   11.28
  73.197  11.347  87.745  10.855 106.964  10.915 108.213  12.422 113.507  12.052
 116.063  10.605  125.33  10.056 127.774   9.405 128.882   8.444 139.642   8.752
 146.643   8.852 156.245   8.986 169.051   8.775 177.919   8.921 193.423   8.124
 202.606   8.905 207.116  14.302  209.15  14.348 218.146   14.55 226.461   15.09
 231.638  15.225
#Mann= 3 , 0 , 0
       0    .033       0       0    .033       0 231.638    .033       0
Bank Sta=0,231.638
XS Rating Curve= 0 ,0
Exp/Cntr=0.3,0.1

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
Type RM Length L Ch R = 1 ,2911.8  ,9.697,9.697,9.697
BEGIN DESCRIPTION:
Topo1  21219.087
END DESCRIPTION:
XS GIS Cut Line= 3
991361.302722849164988.033750124991252.790927258164948.022681856
991144.279131666164908.011613588
#Sta/Elev= 25
       0   13.78   1.509  13.727   6.436  11.128  16.468  10.919   31.75  10.728
  46.129  11.086  64.355  10.967  70.095  12.134  94.255  11.717  108.73  11.938
 121.969  10.995 127.402    8.98 140.968   9.231  154.04   9.011 170.722    8.37
 177.327   8.033 191.588   7.649 198.588   7.849 198.598   8.349 199.179   9.775
 205.818  13.288 206.459  13.318 217.104  13.819 227.581  14.135 231.306  14.423
#Mann= 3 , 0 , 0
       0    .033       0       0    .033       0 231.306    .033       0
Bank Sta=0,231.306
XS Rating Curve= 0 ,0
Exp/Cntr=0.3,0.1

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
Type RM Length L Ch R = 1 ,2601.5  ,9.943,9.943,9.943
BEGIN DESCRIPTION:
Topo1  21529.303
END DESCRIPTION:
XS GIS Cut Line= 3
991466.993191623164697.173308298991362.395152778164657.772602777
991257.797113934164618.371897255
#Sta/Elev= 30
       0  12.825    3.24  12.635  12.506   10.55   21.48  10.398  36.406  11.407
  49.961  10.213    58.2   9.485  62.211  10.731  68.786   9.147  69.246   7.273
  71.245   6.473  80.176   6.983  82.601   8.247  99.824   8.442 116.369   7.958
 128.222   7.643 137.335   7.306 156.368   6.785 164.368   6.785 164.868   7.785
 166.198   8.684 171.824    9.17 182.461   9.596 194.939   9.026 202.579    9.72
 210.243   7.964  214.23   8.262 217.164  12.675  218.85   12.72 223.545  12.845
#Mann= 3 , 0 , 0
       0    .033       0       0    .033       0 223.545    .033       0
Bank Sta=0,223.545
XS Rating Curve= 0 ,0
Exp/Cntr=0.3,0.1

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
Type RM Length L Ch R = 1 ,2462.3  ,9.991,9.991,9.991
BEGIN DESCRIPTION:
Topo1  21668.587
END DESCRIPTION:
XS GIS Cut Line= 3
 991528.32990311164576.332601993991413.806378267164528.442563961
991299.282853424164480.552525929
#Sta/Elev= 28
       0  11.998    2.66  11.912   9.739  10.832  26.319  10.269  35.542  10.111
   47.19  11.065  54.089  10.353  55.476   9.088  58.316   8.491  58.602   7.107
  60.602   5.107  69.387   5.903  77.387   6.203  84.379   6.741  88.154   6.574
  100.84   7.018 114.798   7.804 127.431   8.255 141.345   8.571 155.206   8.427
 170.561   8.864 182.049   8.337 197.553   7.895   207.8   7.696 215.086  12.863
 216.327  12.867 230.416  12.917 248.266  13.056
#Mann= 3 , 0 , 0
       0    .033       0       0    .033       0 248.266    .033       0
Bank Sta=0,248.266
XS Rating Curve= 0 ,0
Exp/Cntr=0.3,0.1

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
Type RM Length L Ch R = 1 ,1992.7  ,9.814,9.814,9.814
BEGIN DESCRIPTION:
Topo1  22138.139
END DESCRIPTION:
XS GIS Cut Line= 3
991730.781580663164168.321163344 991617.98964623164116.443485833
991505.197711797164064.565808323
#Sta/Elev= 23
       0  16.012    2.23  15.948  12.778  10.304  17.001  10.177  46.628   9.585
  46.706   9.062  56.784   9.138  67.246   9.258  73.724   7.445  85.106   7.257
 107.584   7.028 113.757   8.061 133.301   7.644 150.063   7.265 168.113   6.001
 186.489   5.616 196.009    5.19 214.907    4.48 224.908   4.784 229.465   5.642
  236.61  14.988 237.468  14.985   248.3  14.953
#Mann= 3 , 0 , 0
       0    .033       0       0    .033       0   248.3    .033       0
Bank Sta=0,248.3
XS Rating Curve= 0 ,0
Exp/Cntr=0.3,0.1

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
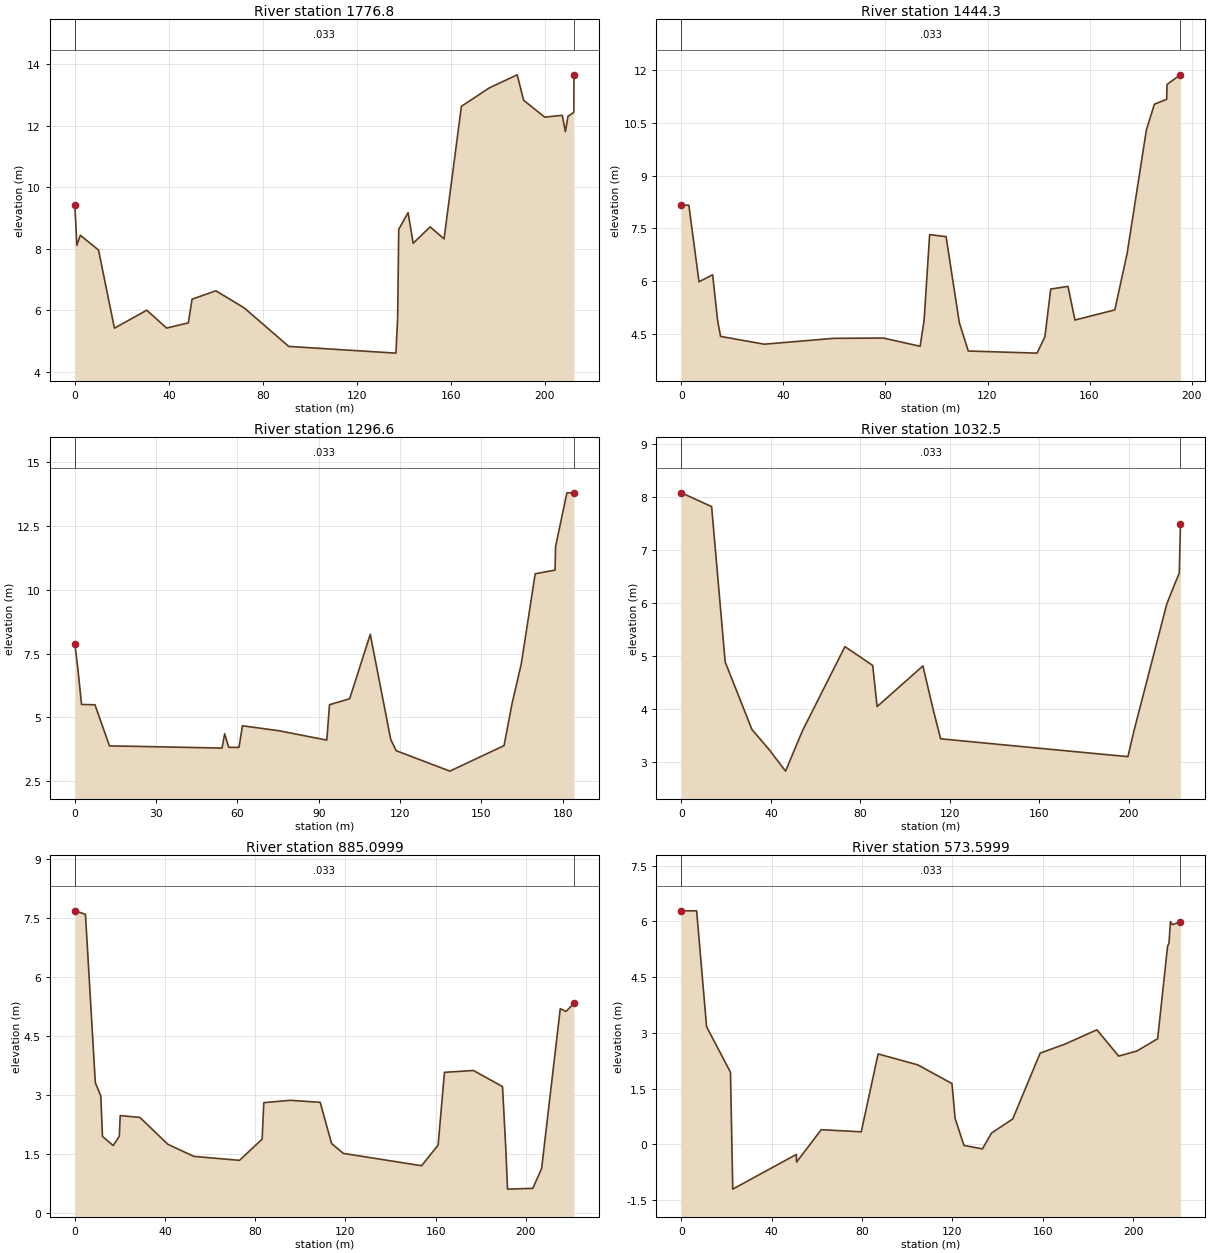
Type RM Length L Ch R = 1 ,1776.8  ,9.779,9.779,9.779
BEGIN DESCRIPTION:
Topo1  22354.010
END DESCRIPTION:
XS GIS Cut Line= 3
991771.532405525163931.880453654991668.373508291163906.505966838
991565.214611056163881.131480022
#Sta/Elev= 29
       0   9.422    .831   8.112   2.325   8.438  10.066   7.959  16.847   5.419
   30.61   6.002  39.057   5.421  48.308    5.59  49.885   6.359  60.032   6.633
  72.014   6.082  91.057   4.825 136.693   4.607 137.428   5.785 137.881    8.63
 141.854   9.175 144.022   8.177 151.243    8.71 157.169   8.321 164.559  12.629
  176.44  13.229 188.316  13.653  191.04  12.827 200.019  12.278 207.516  12.337
 208.837  11.805 209.944  12.304 212.441  12.436 212.467  13.653
#Mann= 3 , 0 , 0
       0    .033       0       0    .033       0 212.467    .033       0
Bank Sta=0,212.467
XS Rating Curve= 0 ,0
Exp/Cntr=0.3,0.1

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
Type RM Length L Ch R = 1 ,1444.3  ,9.847,9.847,9.847
BEGIN DESCRIPTION:
Topo1  22686.564
END DESCRIPTION:
XS GIS Cut Line= 3
991855.168081135163630.619592172991766.342728049163589.649219338
991677.517374963163548.678846504
#Sta/Elev= 29
       0   8.157    2.92   8.157   6.901   5.979  12.247   6.177  14.189   4.882
  15.352   4.424  32.454   4.202   59.74   4.369  79.113   4.377  93.586   4.143
  95.146   4.885   97.31    7.32 103.752   7.263 108.949   4.815 112.456   4.008
 139.421   3.948   142.5   4.415 144.779   5.771 151.548   5.847 154.271    4.89
 169.905   5.178 174.741   6.788 182.276    10.3 183.074  10.485 185.425  11.031
 190.235   11.17 190.377  11.593 195.544  11.867 195.637  11.867
#Mann= 3 , 0 , 0
       0    .033       0       0    .033       0 195.637    .033       0
Bank Sta=0,195.637
XS Rating Curve= 0 ,0
Exp/Cntr=0.3,0.1

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
Type RM Length L Ch R = 1 ,1296.6  ,9.781,9.781,9.781
BEGIN DESCRIPTION:
Topo1  22834.213
END DESCRIPTION:
XS GIS Cut Line= 3
991917.192764657163496.881831314991833.598992452163458.269017611
991750.005220248163419.656203908
#Sta/Elev= 28
       0   7.881    1.12   6.891   2.457   5.509   7.421   5.496  12.775   3.883
  22.956   3.866  54.302   3.798  55.272   4.358  56.787   3.828  60.562   3.825
  61.844   4.673   75.28   4.478   92.97   4.111  93.962   5.498 101.407   5.733
 109.008   8.258 116.566   4.133 118.593   3.695 138.373   2.895 158.373   3.895
  161.31   5.535 164.737   7.103  169.86  10.632 170.808  10.651 177.196  10.776
 177.395  11.703 181.564  13.805 184.161  13.805
#Mann= 3 , 0 , 0
       0    .033       0       0    .033       0 184.161    .033       0
Bank Sta=0,184.161
XS Rating Curve= 0 ,0
Exp/Cntr=0.3,0.1

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
Type RM Length L Ch R = 1 ,1032.5  ,9.827,9.827,9.827
BEGIN DESCRIPTION:
Topo1  23098.331
END DESCRIPTION:
XS GIS Cut Line= 3
992016.104159065163241.842050536991910.147781843163207.019709009
991804.191404621163172.197367482
#Sta/Elev= 23
       0   8.081  13.511   7.821  19.563   4.886  31.531   3.608  39.112   3.235
  46.556   2.822  54.066   3.581  73.103   5.175  85.501   4.819  87.491   4.042
 107.955    4.81 112.501   3.992 115.876   3.433 151.146    3.29 187.146   3.145
 199.582   3.096 202.354   3.596 216.949    5.98  219.25   6.225  220.73   6.382
 221.449   6.451 222.548    6.57 223.063     7.5
#Mann= 3 , 0 , 0
       0    .033       0       0    .033       0 223.063    .033       0
Bank Sta=0,223.063
XS Rating Curve= 0 ,0
Exp/Cntr=0.3,0.1

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
Type RM Length L Ch R = 1 ,885.0999,9.734,9.734,9.734
BEGIN DESCRIPTION:
Topo1  23245.782
END DESCRIPTION:
XS GIS Cut Line= 3
992072.037776852163120.663651538 991971.81780053163073.738221045
991871.597824208163026.812790552
#Sta/Elev= 30
       0   7.691   4.693   7.602   9.073   3.313  11.516   2.973   12.24   1.945
  16.987   1.713   19.71    1.95  20.117   2.476  28.854   2.429  41.263   1.744
  52.757   1.437      73   1.336  83.047   1.876  83.788   2.805  95.524   2.865
  108.79   2.814 113.852   1.764 119.067   1.513 153.765   1.199 161.099   1.725
 163.901   3.577 176.748   3.625 189.645   3.215  191.13   1.615 191.881    .603
 203.092    .623 207.002   1.131 215.264   5.199 217.782   5.129 221.323   5.333
#Mann= 3 , 0 , 0
       0    .033       0       0    .033       0 221.323    .033       0
Bank Sta=0,221.323
XS Rating Curve= 0 ,0
Exp/Cntr=0.3,0.1

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
Type RM Length L Ch R = 1 ,573.5999,9.657,9.657,9.657
BEGIN DESCRIPTION:
Topo1  23557.293
END DESCRIPTION:
XS GIS Cut Line= 3
992182.867965317 162799.76525316992073.889455462162781.477326611
991964.910945607162763.189400061
#Sta/Elev= 29
       0   6.286   6.757   6.286  11.146   3.167  21.745   1.938  22.193     .52
  22.739  -1.208  50.931   -.273  51.005   -.479  61.932    .393  79.651    .335
  87.109   2.432 104.665   2.139  119.83   1.634 121.181    .704 125.124   -.031
 133.307   -.124 137.383    .304 146.736    .682 158.862   2.453 170.051   2.702
 183.997   3.082 193.639   2.374  201.76   2.512 210.901   2.842 215.294   5.331
 215.935   5.421 216.556   5.993 217.525   5.914 221.004   5.993
#Mann= 3 , 0 , 0
       0    .033       0       0    .033       0 221.004    .033       0
Bank Sta=0,221.004
XS Rating Curve= 0 ,0
Exp/Cntr=0.3,0.1

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
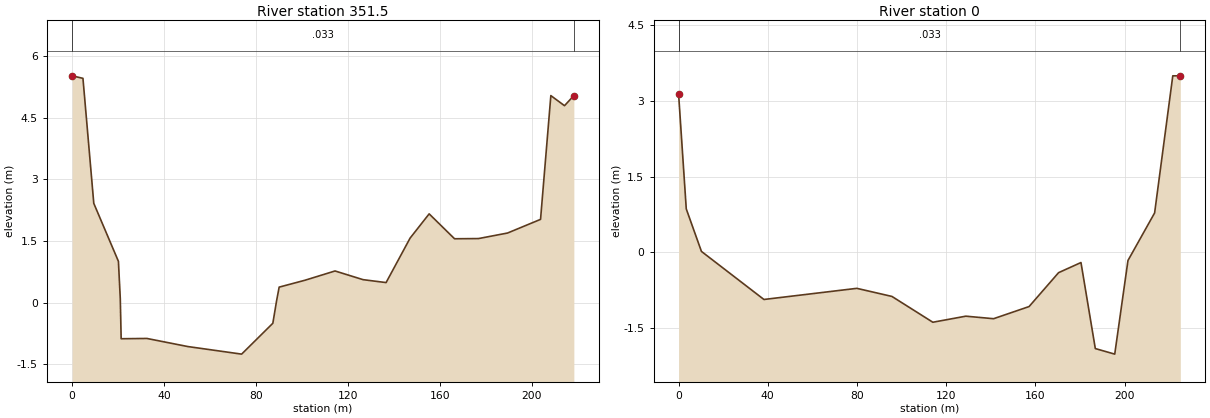
Type RM Length L Ch R = 1 ,351.5   ,9.764,9.764,9.764
BEGIN DESCRIPTION:
Topo1  23779.329
END DESCRIPTION:
XS GIS Cut Line= 3
992211.558480912 162574.37129195992103.186088181162561.325206371
 991994.81369545162548.279120791
#Sta/Elev= 26
       0   5.526   4.709   5.465   9.426   2.417  20.142   1.004  20.956    .091
  21.334   -.883  32.531   -.876  50.303  -1.073  73.755  -1.258   87.33   -.506
  88.957     .04  90.081    .375 101.378    .544 114.387    .769 126.613    .557
 136.608    .486 147.056    1.57 155.347   2.161 166.398   1.554 176.849   1.559
 189.454   1.694 203.815   2.027 208.299   5.044  209.35       5 214.241   4.798
 218.309   5.044
#Mann= 3 , 0 , 0
       0    .033       0       0    .033       0 218.309    .033       0
Bank Sta=0,218.309
XS Rating Curve= 0 ,0
Exp/Cntr=0.3,0.1

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
Type RM Length L Ch R = 1 ,0       ,,,
BEGIN DESCRIPTION:
Topo1  24130.886
END DESCRIPTION:
XS GIS Cut Line= 3
992167.268828684162186.125633047         992060.         162220.
991952.731171316162253.874366953
#Sta/Elev= 18
       0    3.13    3.44     .86   10.24     .02   38.27    -.93   79.92    -.71
   95.67    -.87  114.01   -1.38  128.78   -1.26  141.24   -1.31  157.16   -1.07
  170.39     -.4  180.43     -.2  186.86    -1.9  195.57   -2.01   201.5    -.16
  213.45     .78   221.6    3.49  224.98    3.49
#Mann= 3 , 0 , 0
       0    .033       0       0    .033       0  224.98    .033       0
Bank Sta=0,224.98
XS Rating Curve= 0 ,0
Exp/Cntr=0.3,0.1
Stream Node=Var             ,Reach 1         , 24130.8 , 0 ,Upstream end
Stream Node=Var             ,Reach 1         , 0 , 1 ,Downstream end
LCMann Table=0

Chan Stop Cuts=-1
Use User Specified Reach Order=0
Composite Channel Slope=5

--- Var.g02 (geometry) ---

Geom Title=Var_Weir
Program Version=5.01

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
River Reach=Var             ,Reach 1

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
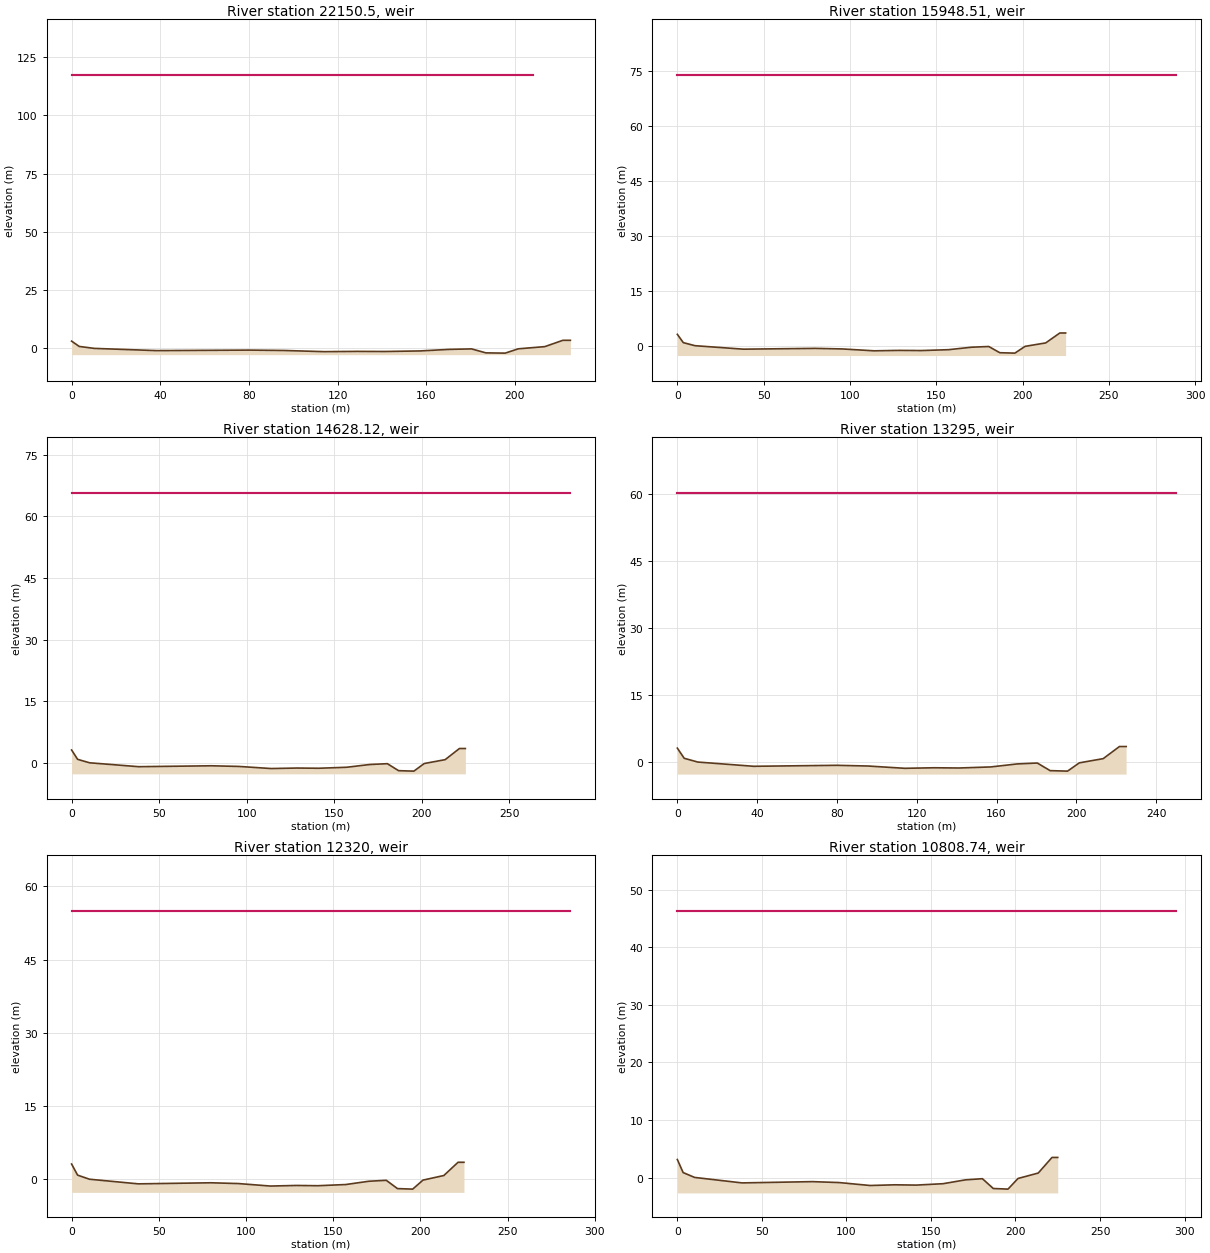
Type RM Length L Ch R = 5 ,22150.5 ,,,
IW Pilot Flow=0
#Inline Weir SE= 2
       0  117.35     208  117.35
IW Dist,WD,Coef,Skew,MaxSub,Min_El,Is_Ogee,SpillHt,DesHd
6.85,3,1.4,0,0.98,, 0 ,,,0,0,
Inline Weir Flap Gates= 0

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
Type RM Length L Ch R = 5 ,15948.51,,,
IW Pilot Flow=0
#Inline Weir SE= 2
       0      74     289      74
IW Dist,WD,Coef,Skew,MaxSub,Min_El,Is_Ogee,SpillHt,DesHd
6.67,3,1.4,0,0.98,, 0 ,,,0,0,
Inline Weir Flap Gates= 0

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
Type RM Length L Ch R = 5 ,14628.12,,,
IW Pilot Flow=0
#Inline Weir SE= 2
       0    65.7     285    65.7
IW Dist,WD,Coef,Skew,MaxSub,Min_El,Is_Ogee,SpillHt,DesHd
6.97,3,1.4,0,0.98,, 0 ,,,0,0,
Inline Weir Flap Gates= 0

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
Type RM Length L Ch R = 5 ,13295   ,,,
IW Pilot Flow=0
#Inline Weir SE= 2
       0    60.2     250    60.2
IW Dist,WD,Coef,Skew,MaxSub,Min_El,Is_Ogee,SpillHt,DesHd
6.94,3,1.4,0,0.98,, 0 ,,,0,0,
Inline Weir Flap Gates= 0

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
Type RM Length L Ch R = 5 ,12320   ,,,
IW Pilot Flow=0
#Inline Weir SE= 2
       0      55     286      55
IW Dist,WD,Coef,Skew,MaxSub,Min_El,Is_Ogee,SpillHt,DesHd
6.86,3,1.4,0,0.98,, 0 ,,,0,0,
Inline Weir Flap Gates= 0

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
Type RM Length L Ch R = 5 ,10808.74,,,
IW Pilot Flow=0
#Inline Weir SE= 2
       0    46.3     295    46.3
IW Dist,WD,Coef,Skew,MaxSub,Min_El,Is_Ogee,SpillHt,DesHd
6.97,3,1.4,0,0.98,, 0 ,,,0,0,
Inline Weir Flap Gates= 0

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